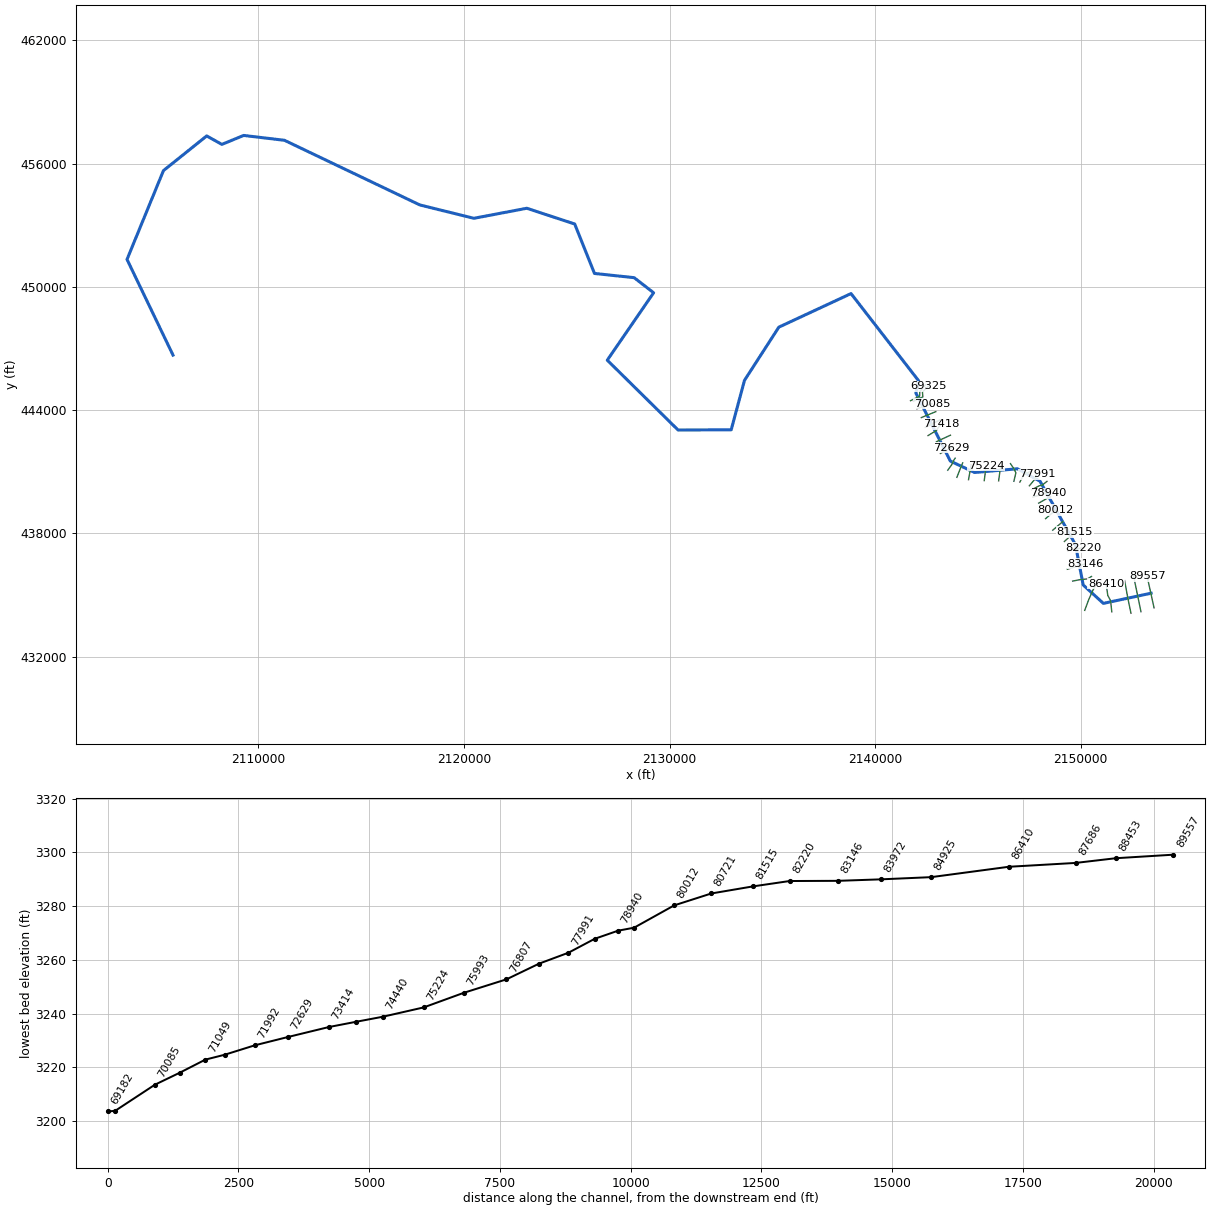
--- NFKCHERRYRV.prj (project) ---

Proj Title=NFKCHERRYRV
Current Plan=p01
Default Exp/Contr=0,0
English Units
Geom File=g01
Flow File=f01
Plan File=p01
BEGIN DESCRIPTION:
Stream Name- North Fork Cherry River
Flood Zone: Zone A
Greenbrier County, WV
County-Wide Study
WVDHSEM-2018-3, Flood Risk Project
HEC-RAS Version: 5.0.7
General Notes:
For the Hydrology Regression was used.
END DESCRIPTION:
DSS Export Rating Curves= 0
DSS Export Rating Curve Sorted= 0
DSS Export Volume Flow Curves= 0
DXF OffsetX= 0
DXF OffsetY= 0
DXF ScaleX= 0
DXF ScaleY= 0

--- NFKCHERRYRV.p01 (plan) ---

Plan Title=Floodplain
Program Version=4.00
Geom File=g01
Flow File=f01
K Sum by GR=0
Std Step Tol=0.01
Critical Tol=0.01
Num of Std Step Trials=20
Max Error Tol=0.3
Flow Tol Ratio=0.001
Split Flow NTrial=30
Split Flow Tol=0.02
Split Flow Ratio=0.02
Log Output Level=0
Friction Slope Method=1
Unsteady Friction Slope Method=2
Unsteady Bridges Friction Slope Method=1
Global Log Level=0
CheckData=False
Run HTab=0
Run UNet=0
Run PostProcess=0
UNET Theta=0
UNET Theta Warmup=0
UNET ZTol=0
UNET ZSATol=0
UNET MxIter=0
UNET MaxInSteps=0
UNET DtIC=0
UNET DtMin=0
UNET MaxCRTS=0
UNET WFStab=0
UNET SFStab=0
UNET WFX=0
UNET SFX=0
UNET DSS MLevel=0
UNET DZMax Abort=0
UNET Convert EG Bridges=0
UNET Use Existing IB Tables=0
UNET Froude Limit=0
UNET Froude Power=0
Write IC File=0
Echo Input=False
Echo Output=False
Write Detailed=0

--- NFKCHERRYRV.f01 (steady flow) ---

Flow Title=NFF Regression Equation
Program Version=5.07
Number of Profiles= 6
Profile Names=f1p,f10p,f4p,f2p,f02p,f1pplus
River Rch & RM=NFKCHERRYRV,Main            ,89557
     812     435     574     689    1130    1200
River Rch & RM=NFKCHERRYRV,Main            ,84925
    1460     799    1040    1240    2000    2160
River Rch & RM=NFKCHERRYRV,Main            ,83972
    1640     904    1180    1400    2250    2430
River Rch & RM=NFKCHERRYRV,Main            ,77991
    1870    1040    1350    1600    2560    2770
River Rch & RM=NFKCHERRYRV,Main            ,73414
    2120    1180    1530    1820    2890    3140
River Rch & RM=NFKCHERRYRV,Main            ,67836
    2400    1340    1740    2060    3260    3550
River Rch & RM=NFKCHERRYRV,Main            ,64865
    2690    1510    1950    2310    3650    3970
River Rch & RM=NFKCHERRYRV,Main            ,58475
    3010    1690    2180    2580    4070    4450
River Rch & RM=NFKCHERRYRV,Main            ,50236
    3350    1890    2440    2880    4520    4950
River Rch & RM=NFKCHERRYRV,Main            ,38986
    3900    2220    2850    3360    5260    5770
River Rch & RM=NFKCHERRYRV,Main            ,30637
    4360    2500    3190    3760    5870    6460
Boundary for River Rch & Prof#=NFKCHERRYRV,Main            , 1
Up Type= 0
Dn Type= 1
Dn Known WS=2235.5
Boundary for River Rch & Prof#=NFKCHERRYRV,Main            , 2
Up Type= 0
Dn Type= 1
Dn Known WS=2232.5
Boundary for River Rch & Prof#=NFKCHERRYRV,Main            , 3
Up Type= 0
Dn Type= 1
Dn Known WS=2233.5
Boundary for River Rch & Prof#=NFKCHERRYRV,Main            , 4
Up Type= 0
Dn Type= 1
Dn Known WS=2234.5
Boundary for River Rch & Prof#=NFKCHERRYRV,Main            , 5
Up Type= 0
Dn Type= 1
Dn Known WS=2238.5
Boundary for River Rch & Prof#=NFKCHERRYRV,Main            , 6
Up Type= 0
Dn Type= 1
Dn Known WS=2240
DSS Import GetInterval= 0
DSS Import GetPeak= 0
DSS Import FillOption= 0

--- NFKCHERRYRV.g01 (geometry) ---

Geom Title=USGS 10m DEM
Program Version=5.07

River Reach=NFKCHERRYRV     ,Main
Reach XY= 30
2153419.53221484435091.382550838     2151098.711      434597.183
     2150116.678      435492.901      2149740.08      437457.762
     2148016.805      440541.706     2146915.061      441146.566
     2144834.657      440968.204     2143658.098      441520.395
     2141979.878       444834.08     2142116.202      445427.828
     2138826.692       449673.97     2135315.468       448039.69
     2133645.621       445451.31     2132999.237      443045.009
     2130415.197      443033.617     2126971.381      446432.914
     2129225.893      449713.826     2128278.779       450448.11
     2126350.647      450653.109     2125387.069      453059.873
      2123058.51      453825.932     2120485.729      453337.115
     2117855.602      453987.607     2111271.931      457133.766
     2109290.064      457369.768     2108225.105      456933.932
     2107492.466      457347.127        2105388.      455659.062
     2103615.879      451336.725      2105852.64      446679.815

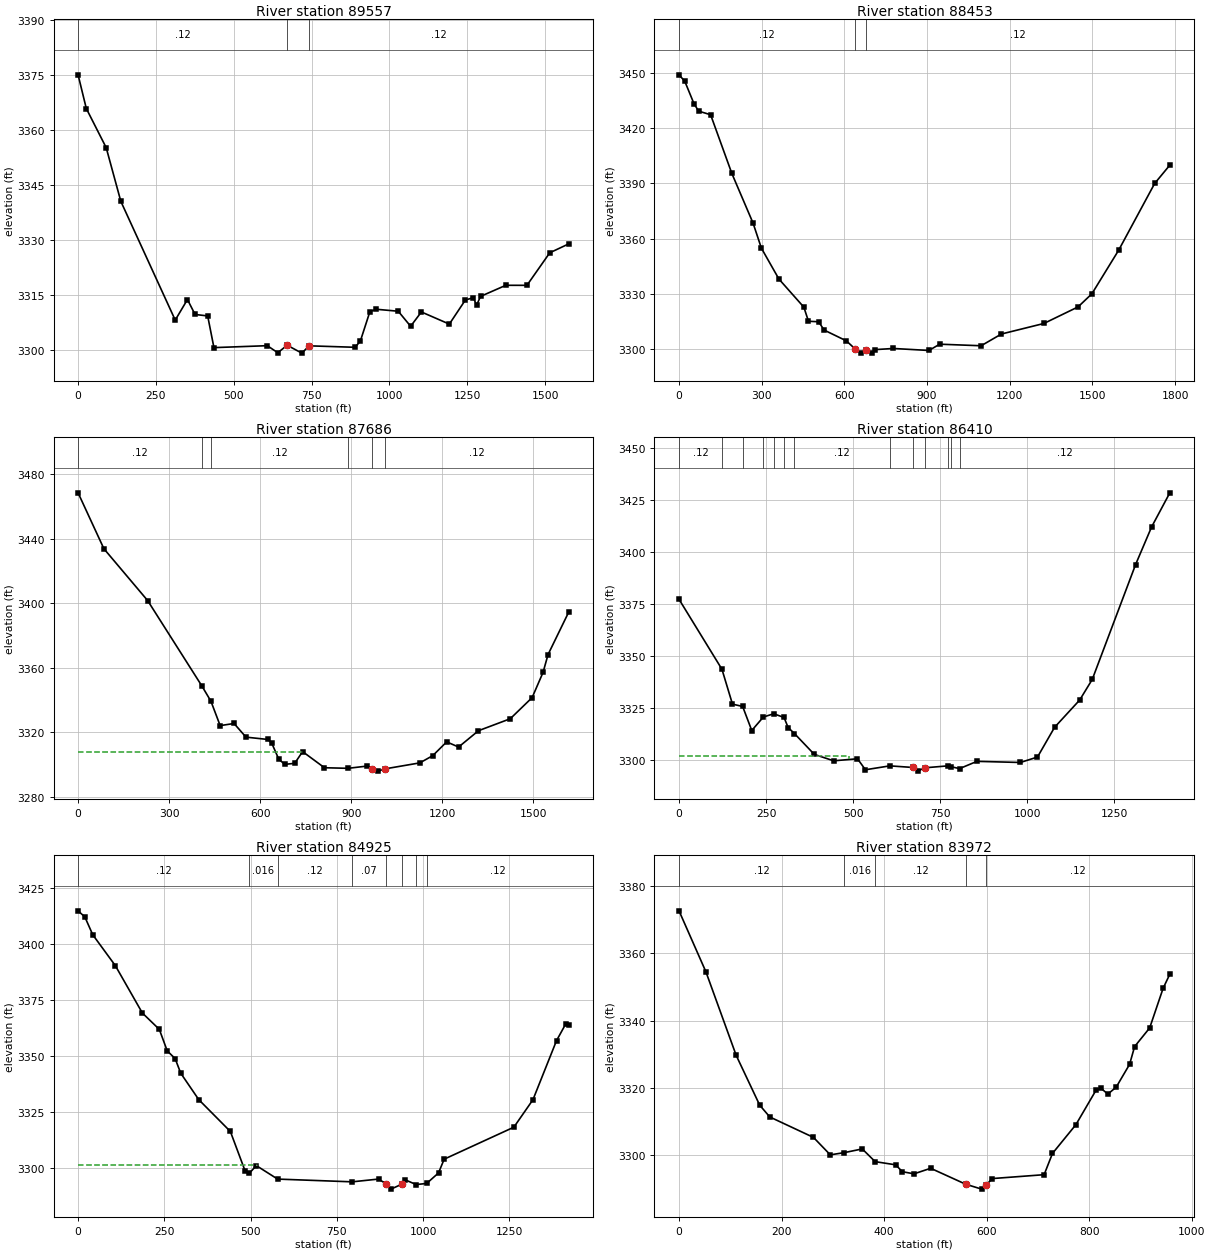
Type RM Length L Ch R = 1 ,89557   ,1028,1104.1,1083.6
XS GIS Cut Line= 2
2153563.96152684434379.5356123112153224.10975559435918.699006059
#Sta/Elev= 30
       0 3375.02    26.4 3365.84    90.3 3355.16   137.3 3340.53     312 3308.16
   351.2 3313.77   375.7  3309.7   416.2  3309.3   436.3 3300.66   607.7 3301.19
   641.3 3299.27   671.5 3301.31   718.6 3299.16     742 3301.15   889.9 3300.75
   906.7 3302.49     937 3310.43   957.1 3311.12  1028.2 3310.58    1068 3306.48
  1102.5 3310.38  1192.3 3307.07  1243.7 3313.63  1269.6 3314.29  1279.7 3312.19
  1292.4 3314.62  1373.7 3317.65  1441.5 3317.64  1514.8 3326.511576.237 3328.96
#Mann= 3 , 0 , 0
       0     .12       0   671.5     .04       0     742     .12       0
Bank Sta=671.5,742
XS Rating Curve= 0 ,0
Exp/Cntr(USF)=0,0
Exp/Cntr=0.3,0.1

Type RM Length L Ch R = 1 ,88453   ,726.6,767.2,746.4
XS GIS Cut Line= 2
2152926.38836921434191.3532265792152566.87575169435935.551160005
#Sta/Elev= 30
       0 3448.93    20.9 3445.43    54.1 3433.32    71.1 3429.22   114.6 3427.27
   191.7 3395.37   268.7 3368.41   298.9 3354.81   362.5 3338.05     453 3322.78
   469.7 3315.14   506.6 3314.88   526.5 3310.36   607.1 3304.51   637.7 3300.29
   660.7 3297.84   677.4 3299.72   700.9 3297.98   710.9 3299.74   777.9 3300.37
   906.5 3299.28     946 3302.69  1096.1 3301.84  1169.8 3308.22  1323.9 3313.94
  1447.9 3322.94  1498.1 3330.06  1595.3 3353.74  1725.9 3389.961780.864 3399.91
#Mann= 3 ,-1 , 0
       0     .12       0   637.7     .04       0   677.4     .12       0
Bank Sta=637.7,677.4
XS Rating Curve= 0 ,0
Exp/Cntr(USF)=0,0
Exp/Cntr=0.3,0.1

Type RM Length L Ch R = 1 ,87686   ,1243,1276.1,1252
XS GIS Cut Line= 3
     2152441.389      434116.218     2152297.449      434805.385
       2152131.7      435703.918
#Sta/Elev= 30
       0 3468.31    85.1 3433.71   229.2 3401.66  407.68 3348.89  437.85 3339.35
   468.3 3324.26   514.1 3325.57   553.4 3317.12   625.4 3315.69   638.6 3313.28
   661.5 3303.48   681.1 3300.28   713.9 3300.91   740.1 3308.16   812.1 3298.19
  889.59 3297.83   952.9 3299.22   969.3 3297.35     989 3296.09  1011.9  3297.5
  1126.5  3301.2  1169.1 3305.68  1214.9 3314.19  1254.2    3311  1319.7  3321.1
  1424.5 3328.51  1496.6  3341.6  1532.6 3357.22    1549 3368.22  1617.7 3394.73
#Mann= 6 ,-1 , 0
       0     .12       0  407.68    .016       0  437.85     .12       0
  889.59     .07       0   969.3     .04       0  1011.9     .12       0
#XS Ineff= 2 , 0
          743.48 3307.74
Permanent Ineff=
       F       F
Bank Sta=969.3,1011.9
XS Rating Curve= 0 ,0
Exp/Cntr=0.3,0.1

Type RM Length L Ch R = 1 ,86410   ,1441.4,1484.8,1429.7
XS GIS Cut Line= 4
     2151507.961      434186.007      2151449.53      434727.786
     2151312.652      434988.024     2151233.229      435552.436
#Sta/Elev= 30
       0 3377.27  123.24 3343.62   153.4 3326.87  182.65 3325.75   208.8 3314.19
  242.06 3320.67  271.77 3322.24  301.48 3320.46   313.2 3315.62  331.19 3312.75
   388.3 3302.71   443.8 3299.62   512.3  3300.6   535.1 3295.32  605.17 3297.19
   672.3 3296.41   685.4 3294.66     705 3296.25  772.03 3297.19   781.7 3296.74
   805.4 3295.88   855.3 3299.36   979.8 3298.82    1029 3301.43  1078.1 3315.73
  1150.2 3328.85  1186.2 3338.74  1310.7    3394  1356.5 3412.03  1408.9 3428.46
#Mann= 13 ,-1 , 0
       0     .12       0  123.24    .016       0  182.65     .12       0
  242.06    .016       0  271.77     .08       0  301.48     .06       0
  331.19     .12       0  605.17     .07       0   672.3     .04       0
     705     .07       0  772.03     .12       0   781.7     .06       0
   805.4     .12       0
#XS Ineff= 2 , 0
           488.7 3301.92
Permanent Ineff=
       F       F
Bank Sta=672.3,705
XS Rating Curve= 0 ,0
Exp/Cntr=0.3,0.1

Type RM Length L Ch R = 1 ,84925   ,957.6,953.1,918.8
XS GIS Cut Line= 4
     2150191.986       434257.47     2150390.307       434790.62
     2150598.932       435254.23     2150771.497         435553.
#Sta/Elev= 30
       0 3414.75    19.6 3412.03    42.5  3404.1   107.9 3390.35   186.3 3369.23
   235.4 3361.95   258.3 3352.37   281.2 3348.95   297.5 3342.42   349.8 3330.64
   441.3 3316.47   483.8 3298.97  495.67 3297.77   516.5 3301.28  578.22 3295.27
  794.14 3294.05   870.6 3295.28   893.6 3293.05   906.7  3290.8   939.5  3293.1
     946 3295.07  979.46 3292.84 1010.07 3293.32  1044.4 3298.01  1060.8 3304.14
  1262.8 3318.39  1318.1 3330.63  1386.4 3356.95  1412.5 3364.21  1422.2 3363.93
#Mann= 8 ,-1 , 0
       0     .12       0  495.67    .016       0  578.22     .12       0
  794.14     .07       0   893.6     .04       0   939.5     .07       0
  979.46     .06       0 1010.07     .12       0
#XS Ineff= 2 , 0
          517.35 3301.63
Permanent Ineff=
       F       F
Bank Sta=893.6,939.5
XS Rating Curve= 0 ,0
Exp/Cntr=0.3,0.1

Type RM Length L Ch R = 1 ,83972   ,812.9,826.1,827.2
XS GIS Cut Line= 4
     2149604.747       435681.78     2149965.332      435751.322
      2150318.19       435787.38     2150521.663      435905.858
#Sta/Elev= 30
       0 3372.65    52.5 3354.52   111.5 3329.72   157.4 3314.92   177.1 3311.42
   262.3 3305.35   295.1 3300.17  322.67 3300.84   357.4 3301.93  382.63 3298.15
   422.6 3297.21   435.6 3295.17   458.3 3294.53   490.9 3296.18   559.2 3291.45
   590.4 3289.99   598.3 3291.11   611.3 3293.13   712.2 3294.28   728.5  3300.6
   774.2 3309.14   813.5 3319.39   823.3 3319.93   836.4 3318.22   852.7 3320.26
   878.9 3327.05   888.7 3332.33   918.1 3337.87   944.3 3349.64   957.4 3353.83
#Mann= 5 ,-1 , 0
       0     .12       0  322.67    .016       0  382.63     .12       0
   559.2     .04       0   598.3     .12       0
Bank Sta=559.2,598.3
XS Rating Curve= 0 ,0
Exp/Cntr=0.3,0.1

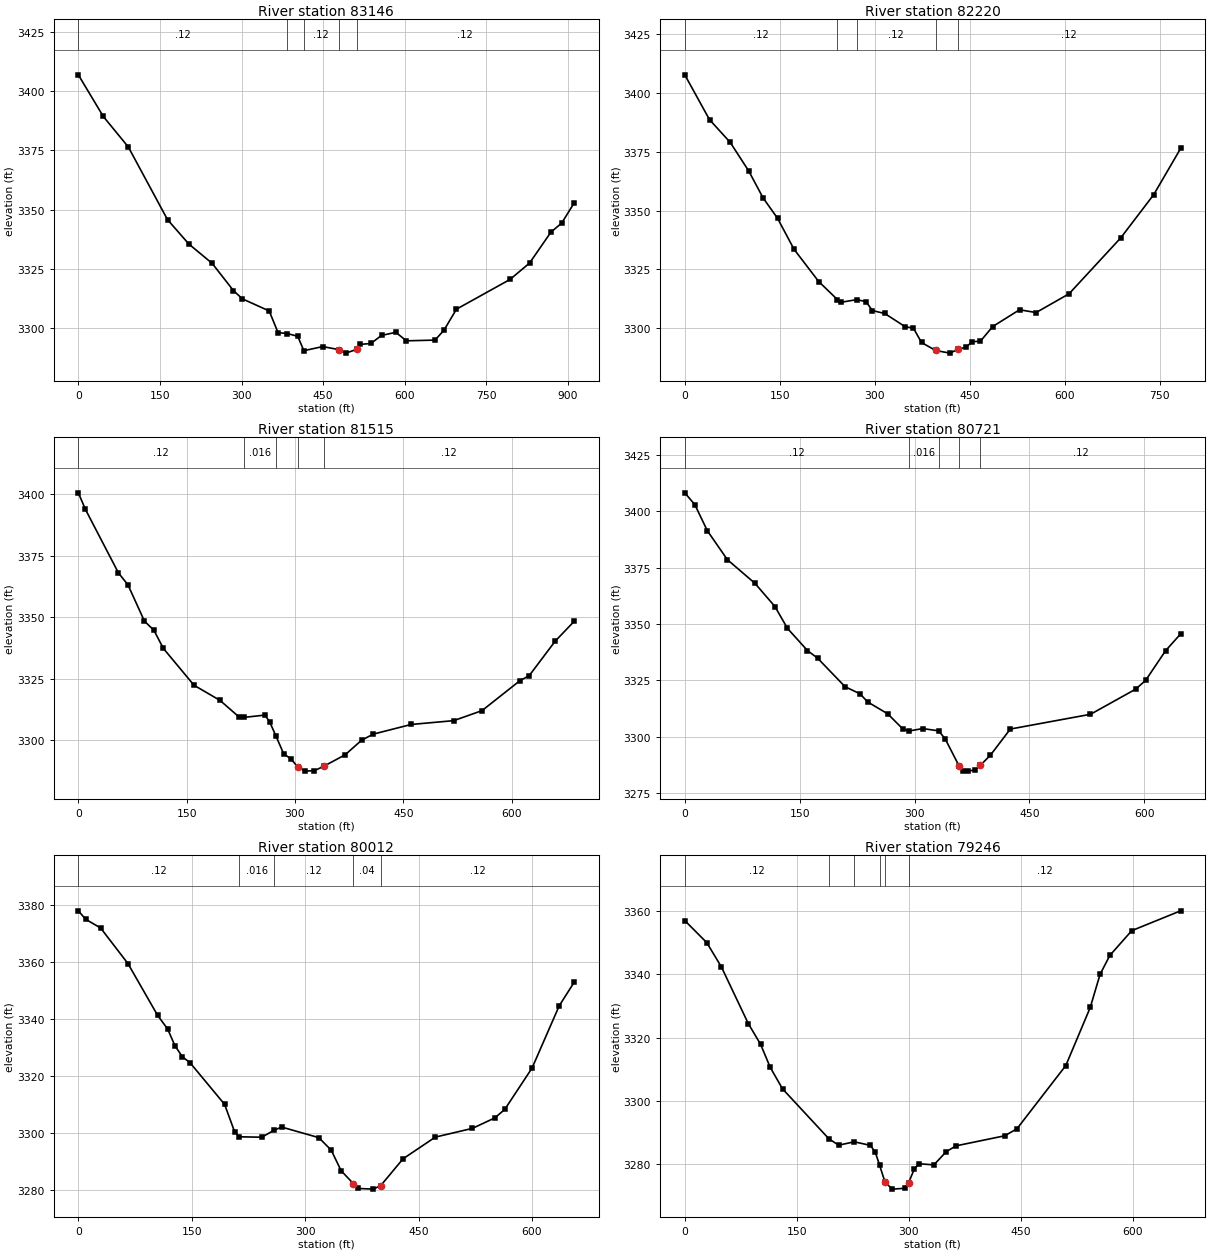
Type RM Length L Ch R = 1 ,83146   ,915.7,925.5,919.1
XS GIS Cut Line= 2
     2149347.187      436258.716     2150220.317      436518.853
#Sta/Elev= 30
       0 3406.94    45.9 3389.35    91.8 3376.49   163.9 3345.78   203.2 3335.47
   245.8 3327.36   285.1 3315.81   301.5 3312.34   350.7 3307.24     367 3298.08
  383.61 3297.71   403.1 3296.56  414.43 3290.46     449 3292.19   478.5 3290.93
   491.6 3289.43   511.2    3291   517.8 3293.11   537.5  3293.5   557.1  3296.9
   583.3 3298.21     603 3294.63   655.4 3294.93   671.8 3299.07   694.8 3307.98
   793.1 3320.52   829.1 3327.44   868.5 3340.54   888.1 3344.32   911.1 3352.83
#Mann= 5 ,-1 , 0
       0     .12       0  383.61    .016       0  414.43     .12       0
   478.5     .04       0   511.2     .12       0
Bank Sta=478.5,511.2
XS Rating Curve= 0 ,0
Exp/Cntr=0.3,0.1

Type RM Length L Ch R = 1 ,82220   ,686.8,705.1,708.4
XS GIS Cut Line= 4
      2149362.64      437149.876     2149697.469      437232.296
     2149827.543      437251.362     2150128.338      437310.507
#Sta/Elev= 30
       0  3407.7      39 3388.64    71.6 3379.01   100.8 3366.88   123.6 3355.36
   146.4 3346.71   172.4 3333.55   211.4  3319.8  241.04 3312.11   247.2 3311.01
  271.45  3312.1   286.3 3311.24     296 3307.46   315.6 3306.22     348 3300.59
   360.9 3300.03   373.7 3293.88   396.1 3290.48   418.6 3289.36   431.4 3290.99
   444.2 3291.94   453.8 3294.23   466.7 3294.41   486.1 3300.66   528.5  3307.8
   554.6 3306.61   606.7  3314.6   688.3 3338.38   740.4 3356.79   782.8 3376.38
#Mann= 5 ,-1 , 0
       0     .12       0  241.04    .016       0  271.45     .12       0
   396.1     .04       0   431.4     .12       0
Bank Sta=396.1,431.4
XS Rating Curve= 0 ,0
Exp/Cntr=0.3,0.1

Type RM Length L Ch R = 1 ,81515   ,791.4,793.9,790
XS GIS Cut Line= 2
     2149202.427      437609.194     2149708.963      438072.804
#Sta/Elev= 30
       0 3400.48     9.8 3393.76    55.6  3367.9    68.7 3363.09    91.6 3348.29
   104.6 3344.65   117.7 3337.26   160.2 3322.26   196.2 3316.11   222.4 3309.41
  229.66  3309.2   258.3 3310.13   264.9 3307.44   273.4 3301.81   284.5 3294.33
   294.3  3292.4   304.1 3288.98   313.9 3287.35     327 3287.54   340.1 3289.36
   369.5 3293.98   392.4 3299.94   408.7 3302.41     461 3306.32   519.9 3307.87
   559.1 3311.95   611.5 3324.09   624.5 3326.18   660.5 3340.21   686.7 3348.23
#Mann= 5 ,-1 , 0
       0     .12       0  229.66    .016       0   273.4     .12       0
   304.1     .04       0   340.1     .12       0
Bank Sta=304.1,340.1
XS Rating Curve= 0 ,0
Exp/Cntr=0.3,0.1

Type RM Length L Ch R = 1 ,80721   ,707,709.2,709
XS GIS Cut Line= 2
     2148635.794      438158.657     2149128.021       438579.34
#Sta/Elev= 30
       0 3408.26    13.1 3403.01    29.4 3391.45    55.6 3378.59    91.6 3368.09
   117.7 3357.79   134.1 3348.07   160.2 3338.25   173.3  3334.9   209.3 3322.19
   228.9 3319.03   238.7 3315.45   264.9 3310.18   284.5 3303.52  292.69 3302.53
   310.7 3303.61  331.54  3302.6   340.1    3299  358.11 3287.06     363 3284.89
   369.5 3284.72   379.4 3285.27   385.9 3287.28     399 3291.75   425.1  3303.4
   529.8 3309.95   588.6 3321.07   601.7 3324.96   627.9  3338.2   647.5 3345.62
#Mann= 5 ,-1 , 0
       0     .12       0  292.69    .016       0  331.54     .12       0
  358.11     .04       0   385.9     .12       0
Bank Sta=358.11,385.9
XS Rating Curve= 0 ,0
Exp/Cntr=0.3,0.1

Type RM Length L Ch R = 1 ,80012   ,767.3,766.2,759.6
XS GIS Cut Line= 2
     2148286.656      438719.567     2148787.468      439143.111
#Sta/Elev= 30
       0 3378.11     9.8 3375.13    29.5 3372.07    65.6 3359.58   104.9 3341.36
   118.1 3336.59   127.9 3330.65   137.7 3326.78   147.6 3324.77   193.5 3310.08
   206.6 3300.53  212.96 3298.68   242.7 3298.54   258.7 3300.95   268.9 3302.11
   318.1 3298.39   334.5    3294   347.6 3286.77     364 3282.17   370.6 3280.52
   390.3 3280.29   400.1 3281.56   429.6 3290.96   472.2 3298.57   521.4 3301.65
     551 3305.34   564.1 3308.31   600.2 3322.84   636.2 3344.76   655.9    3353
#Mann= 5 ,-1 , 0
       0     .12       0  212.96    .016       0   258.7     .12       0
     364     .04       0   400.1     .12       0
Bank Sta=364,400.1
XS Rating Curve= 0 ,0
Exp/Cntr=0.3,0.1

Type RM Length L Ch R = 1 ,79246   ,306.6,305.4,299.3
XS GIS Cut Line= 2
     2147951.827      439475.079     2148529.908      439801.322
#Sta/Elev= 30
       0 3357.04    29.4 3350.06      49 3342.36      85 3324.42   101.4 3317.88
   114.4 3310.54   130.8 3303.76  192.98 3287.91     206 3285.91   226.9 3286.97
   248.5 3285.85     255 3283.68  260.81 3279.55   268.1 3274.15   277.9 3271.99
   294.3 3272.25  299.55 3273.97   307.4 3278.43   313.9 3280.02   333.5 3279.67
   349.9 3283.83     363 3285.69   428.4 3288.89   444.7 3291.11   510.1 3311.14
   542.8 3329.52   555.9 3339.98     569    3346   598.4 3353.85   663.8 3360.13
#Mann= 6 ,-1 , 0
       0     .12       0  192.98     .08       0   226.9    .016       0
  260.81     .12       0   268.1     .04       0  299.55     .12       0
Bank Sta=268.1,299.55
XS Rating Curve= 0 ,0
Exp/Cntr=0.3,0.1

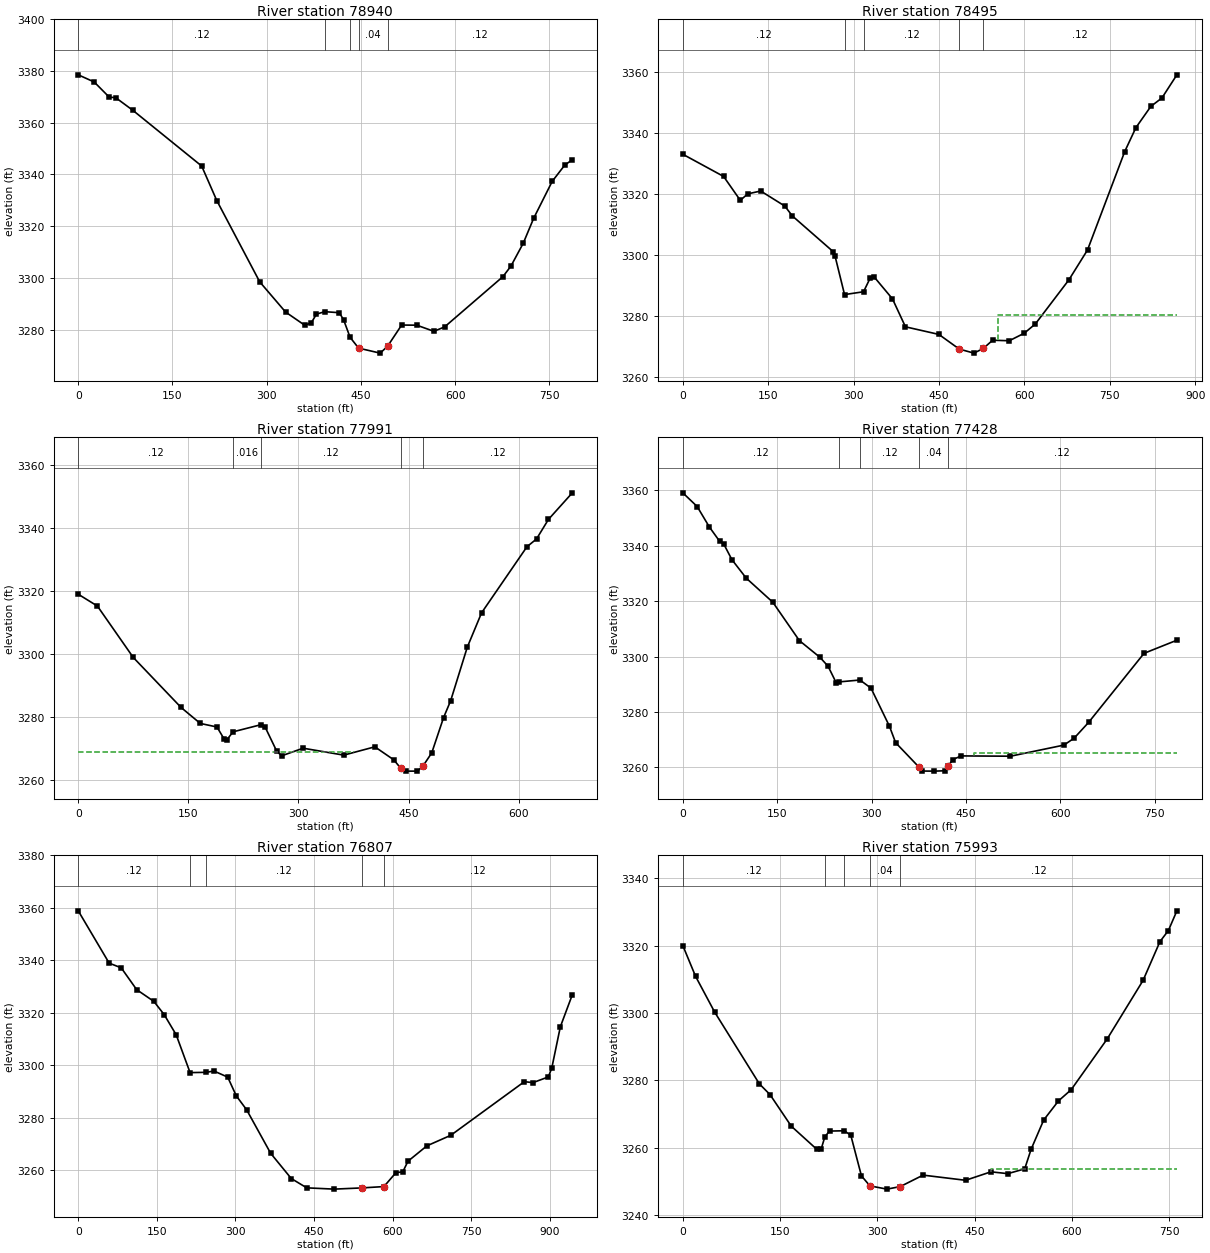
Type RM Length L Ch R = 1 ,78940   ,445.8,445.7,442.1
XS GIS Cut Line= 3
2147664.54357172439768.5372713952148308.11371963439959.696721269
2148422.80938955439950.138748775
#Sta/Elev= 30
       0 3378.51    25.4 3375.74    49.3 3369.88    59.6 3369.68      87 3364.77
   196.5 3343.23   220.5  3329.9   288.9 3298.44     330 3286.78   360.8 3281.62
   371.1 3282.67   379.2 3285.96   392.4 3286.91   415.5 3286.52   422.4 3283.78
   432.7    3277   446.3 3272.81   480.6 3270.88   492.3 3273.51   514.8 3281.74
   538.8 3281.69   566.1 3279.32   583.2 3281.02     676 3300.46   688.7 3304.51
   708.4  3313.4   724.9    3323   754.5 3337.32   774.3 3343.55   786.5  3345.7
#Mann= 5 ,-1 , 0
       0     .12       0   392.4    .016       0   432.7     .12       0
   446.3     .04       0   492.3     .12       0
Bank Sta=446.3,492.3
XS Rating Curve= 0 ,0
Exp/Cntr(USF)=0,0
Exp/Cntr=0.3,0.1

Type RM Length L Ch R = 1 ,78495   ,479.4,503.6,518.5
XS GIS Cut Line= 4
     2147602.689      440121.842     2147977.583      440319.305
     2148120.672      440350.785     2148355.339      440533.939
#Sta/Elev= 30
       0  3333.1    71.7 3325.82     101 3317.98   114.1 3320.11   136.9 3321.04
   179.3 3316.09   192.3 3312.89     264 3301.18   267.3 3299.81  284.12 3287.07
   317.5    3288   329.2 3292.51   335.7 3292.95   368.3 3285.67   391.1  3276.5
   449.8 3274.01   485.6  3269.2   511.4 3267.87   527.9 3269.41   544.2  3272.1
   573.5 3271.93   599.7 3274.39   619.3 3277.44   678.2  3291.9   710.9  3301.7
   776.3 3333.99   795.9 3341.82   822.1 3348.78   841.7 3351.58   867.9 3359.15
#Mann= 5 ,-1 , 0
       0     .12       0  284.12    .016       0   317.5     .12       0
   485.6     .04       0   527.9     .12       0
#XS Ineff= 2 , 0
                          553.46         3280.29
Permanent Ineff=
       F       F
Bank Sta=485.6,527.9
XS Rating Curve= 0 ,0
Exp/Cntr=0.3,0.1

Type RM Length L Ch R = 1 ,77991   ,575.1,563.3,553.5
XS GIS Cut Line= 4
     2147499.665      440319.305     2147751.502      440622.655
     2147791.567      440765.744     2147863.112      440874.492
#Sta/Elev= 30
       0 3318.86    26.1  3315.1    74.9 3298.79   140.1 3282.89   166.2 3277.83
     189 3276.69   198.8 3272.83     202  3272.5  210.89 3275.16  249.28 3277.45
   254.2 3276.84   270.4 3268.99     277 3267.54   306.3 3269.96   361.7 3267.76
     404  3270.4   429.8 3266.27   439.5 3263.53     446 3262.68   462.1 3262.68
   469.4 3264.25   481.5 3268.47   497.6 3279.67   507.3 3285.06   529.9 3302.03
   549.4 3312.96   611.2 3333.94   624.2  3336.4   640.5 3342.63     673 3351.06
#Mann= 5 ,-1 , 0
       0     .12       0  210.89    .016       0  249.28     .12       0
   439.5     .04       0   469.4     .12       0
#XS Ineff= 2 , 0
          376.09 3268.88
Permanent Ineff=
       F       F
Bank Sta=439.5,469.4
XS Rating Curve= 0 ,0
Exp/Cntr=0.3,0.1

Type RM Length L Ch R = 1 ,77428   ,579.7,621.1,636.4
XS GIS Cut Line= 4
     2147036.056      440499.598     2147193.454        440791.5
     2147287.893      440885.939      2147571.21      441034.752
#Sta/Elev= 30
       0 3359.15    22.8 3354.21    42.3 3346.78    58.5 3341.66      65 3340.69
      78 3335.02   100.8 3328.33   143.1 3319.61   185.3 3305.75   217.8 3299.75
   230.8 3296.52   243.8 3290.53  247.97 3290.83  281.52 3291.52   299.1 3288.58
   328.4 3274.82   338.2 3268.89  375.45 3260.02   380.5 3258.63     400  3258.6
   416.3 3258.73  421.17 3260.35   429.4  3262.8   442.4  3264.1   520.7 3263.99
   605.6    3268   621.9  3270.5   644.8 3276.18     733 3301.16   785.2  3305.9
#Mann= 5 ,-1 , 0
       0     .12       0  247.97    .016       0  281.52     .12       0
  375.45     .04       0  421.17     .12       0
#XS Ineff= 2 , 0
                          462.61         3265.07
Permanent Ineff=
       F       F
Bank Sta=375.45,421.17
XS Rating Curve= 0 ,0
Exp/Cntr=0.3,0.1

Type RM Length L Ch R = 1 ,76807   ,824.1,813.5,803
XS GIS Cut Line= 4
     2146747.015      440539.663     2146844.316      440954.622
     2146724.121      441183.565     2146581.032      441398.198
#Sta/Elev= 30
       0 3358.87      59 3338.93      82 3337.14   111.5 3328.82   144.3 3324.34
   163.9 3319.33   186.9 3311.61  213.37  3297.2   243.7  3297.3     259  3297.8
   285.2 3295.48   301.6 3288.33   321.3 3283.03   367.2 3266.43   406.5 3256.82
     436 3253.27   488.4 3252.78   540.8 3253.24   583.3 3253.75   606.2 3259.06
   619.3 3259.38   629.2 3263.42   665.2 3269.27   710.9  3273.3   851.3 3293.75
   867.6 3293.37     897 3295.55   903.6 3298.94   919.9 3314.65   942.8  3326.9
#Mann= 5 ,-1 , 0
       0     .12       0  213.37    .016       0   243.7     .12       0
   540.8     .04       0   583.3     .12       0
Bank Sta=540.8,583.3
XS Rating Curve= 0 ,0
Exp/Cntr=0.3,0.1

Type RM Length L Ch R = 1 ,75993   ,763.9,769.2,768
XS GIS Cut Line= 3
     2146005.813      440559.695     2146060.187      440966.069
     2146123.146      441312.345
#Sta/Elev= 30
       0    3320    19.7 3310.86    49.2 3300.24   118.1 3278.98   134.5  3275.8
   167.3 3266.44   206.6 3259.59   213.2 3259.53  219.18 3263.34   226.3 3264.99
  248.97 3265.08   259.1 3263.75   275.5 3251.71   288.6 3248.74   314.9 3247.78
   335.3 3248.53   370.6 3251.93   436.1  3250.4   475.2 3252.91   501.2 3252.37
   527.3 3253.78   537.1 3259.55   556.6 3268.27   579.4 3273.94     599 3277.26
   654.4 3292.27   709.8 3309.64   735.9 3321.16   748.9 3324.44     762 3330.28
#Mann= 5 ,-1 , 0
       0     .12       0  219.18    .016       0  248.97     .12       0
   288.6     .04       0   335.3     .12       0
#XS Ineff= 2 , 0
                          474.84         3253.69
Permanent Ineff=
       F       F
Bank Sta=288.6,335.3
XS Rating Curve= 0 ,0
Exp/Cntr=0.3,0.1

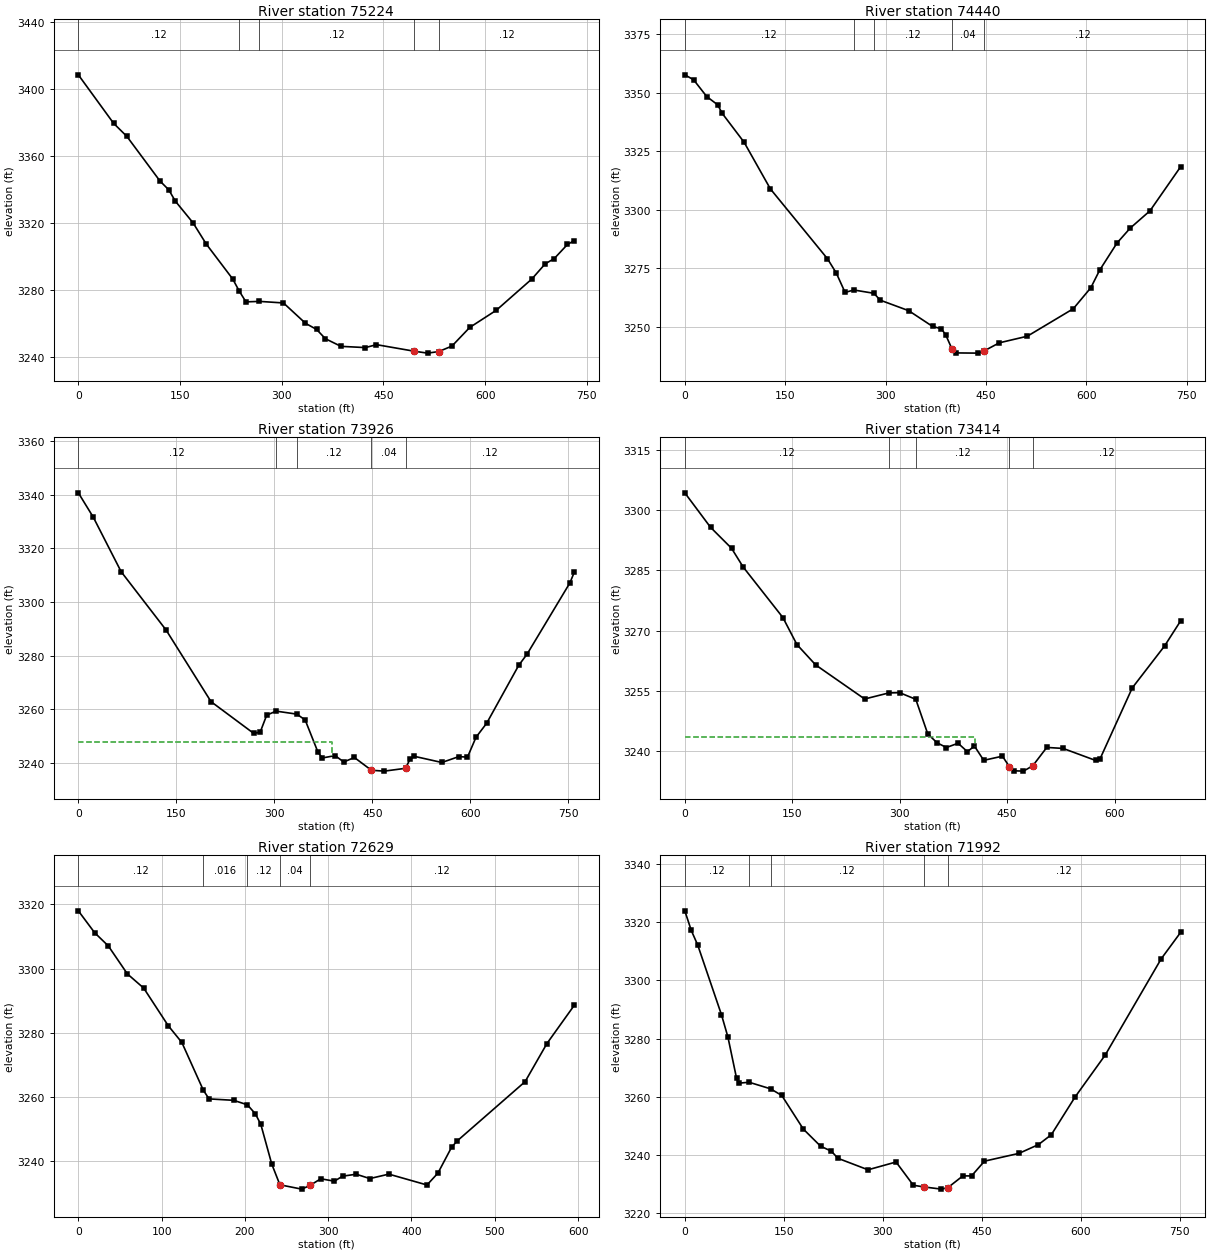
Type RM Length L Ch R = 1 ,75224   ,779.8,784.2,764.6
XS GIS Cut Line= 3
     2145304.675      440571.142     2145350.464      440926.004
     2145381.944      441298.036
#Sta/Elev= 30
       0 3408.66      52 3379.69    71.6 3371.85   120.4  3345.2   133.4 3339.91
   143.1 3333.14   169.1 3320.24   188.7  3307.5   227.7 3286.62  237.28 3279.42
   247.2 3272.96  267.06 3273.25   302.5 3272.32     335 3260.16   351.3  3256.5
   364.4 3250.93   387.3 3246.38   423.3 3245.64   439.7 3247.39   495.4 3243.47
     515 3242.33   531.4 3243.25     551 3246.56   577.2 3257.68   616.5 3267.98
   668.9 3286.68   688.6 3295.74   701.7 3298.78   721.3 3307.27   731.2 3309.55
#Mann= 5 ,-1 , 0
       0     .12       0  237.28    .016       0  267.06     .12       0
   495.4     .04       0   531.4     .12       0
Bank Sta=495.4,531.4
XS Rating Curve= 0 ,0
Exp/Cntr=0.3,0.1

Type RM Length L Ch R = 1 ,74440   ,512.1,513.7,500
XS GIS Cut Line= 4
     2144540.579      440616.931     2144603.538      440968.931
     2144637.879      441109.158     2144663.636      441346.686
#Sta/Elev= 30
       0 3357.55    13.1 3355.46    32.8 3348.28    49.2 3344.74    55.8 3341.15
    88.6  3328.8   127.9 3308.89   213.2  3279.1   226.4 3272.99   239.5 3264.74
  252.56 3265.78  282.57 3264.37     292 3261.44   334.6 3256.95   370.4 3250.21
   383.2 3249.27   389.7 3246.76   399.3 3240.58   405.7 3238.94   437.8 3238.85
   447.4 3239.82   469.9 3243.24   511.8 3246.06   580.5 3257.78   606.7 3266.73
   619.8 3274.18     646 3285.88   665.6 3292.18   695.1 3299.54   740.9 3318.34
#Mann= 5 ,-1 , 0
       0     .12       0  252.56    .016       0  282.57     .12       0
   399.3     .04       0   447.4     .12       0
Bank Sta=399.3,447.4
XS Rating Curve= 0 ,0
Exp/Cntr=0.3,0.1

Type RM Length L Ch R = 1 ,73926   ,509.6,511.9,502.3
XS GIS Cut Line= 3
     2143973.945      440731.402     2144119.896      441103.435
     2144257.262      441435.402
#Sta/Elev= 30
       0 3340.63    22.9 3331.55    65.5 3311.26   134.3 3289.53   203.1 3262.84
   268.6 3250.99   278.4 3251.51   288.3 3257.81  302.74 3259.31  334.47 3258.19
   347.2 3256.01   366.9 3243.95   373.4 3241.86   393.1 3242.74   406.2 3240.36
   422.5 3242.04   448.6 3237.28   468.2 3236.96   500.9 3238.01   507.4 3241.31
     514 3242.49   556.4 3240.18   582.5 3242.38   595.6 3242.16   608.7 3249.58
     625  3254.8     674 3276.35     687  3280.6   752.4 3307.09   758.9 3310.96
#Mann= 5 ,-1 , 0
       0     .12       0  302.74    .016       0  334.47     .12       0
   448.6     .04       0   500.9     .12       0
#XS Ineff= 2 , 0
          388.47  3247.9
Permanent Ineff=
       F       F
Bank Sta=448.6,500.9
XS Rating Curve= 0 ,0
Exp/Cntr=0.3,0.1

Type RM Length L Ch R = 1 ,73414   ,793.6,785,772.7
XS GIS Cut Line= 4
     2143530.368      441077.678     2143730.693      441355.272
     2143810.823      441544.149     2143890.953      441664.344
#Sta/Elev= 30
       0 3304.33    35.9 3295.75    65.2 3290.53    81.5 3285.85   136.9 3273.28
   156.5 3266.55   182.6 3261.49     251    3253  284.76 3254.51   299.9 3254.57
  322.39 3252.92   339.1  3244.3   352.1 3242.09   365.1 3240.92   381.4 3241.98
   394.4 3239.88   404.2 3241.29   417.2 3237.73   443.3 3238.76   453.1 3236.13
   459.6 3235.12   472.6 3235.04   485.6 3236.36   505.2 3240.94     528 3240.69
   573.2 3237.71   579.6 3238.12   624.5 3255.76   669.5 3266.18     692 3272.44
#Mann= 5 ,-1 , 0
       0     .12       0  284.76    .016       0  322.39     .12       0
   453.1     .04       0   485.6     .12       0
#XS Ineff= 2 , 0
           404.8 3243.54
Permanent Ineff=
       F       F
Bank Sta=453.1,485.6
XS Rating Curve= 0 ,0
Exp/Cntr=0.3,0.1

Type RM Length L Ch R = 1 ,72629   ,635.8,637,634.5
XS GIS Cut Line= 2
     2143172.645      441893.287     2143699.214      442170.881
#Sta/Elev= 30
       0 3317.99    19.6 3311.17      36 3307.06    58.9 3298.34    78.5 3293.92
   107.9 3282.23   124.3 3276.99  150.21 3262.05     157 3259.42   186.4 3258.98
  202.94 3257.59   212.6 3254.75   219.1 3251.48   232.2 3239.15     242 3232.67
   268.2 3231.32     278 3232.45   291.1 3234.55   307.4 3233.79   317.2 3235.35
   333.6 3235.96     350 3234.61   372.8 3235.99   418.6 3232.61   431.7  3236.3
   448.1 3244.34   454.6 3246.27   536.4 3264.79   562.6 3276.66   595.3 3288.52
#Mann= 5 ,-1 , 0
       0     .12       0  150.21    .016       0  202.94     .12       0
     242     .04       0     278     .12       0
Bank Sta=242,278
XS Rating Curve= 0 ,0
Exp/Cntr=0.3,0.1

Type RM Length L Ch R = 1 ,71992   ,564.3,574.5,584.2
XS GIS Cut Line= 2
     2142980.906      442465.644     2143662.011      442783.303
#Sta/Elev= 30
       0 3323.94     9.8  3317.2    19.6 3312.16    55.6 3288.19    65.4 3280.49
    78.4 3266.39    81.7 3264.66   97.47 3264.97  130.06 3262.71     147 3260.42
   179.7 3248.85   205.9 3242.96   222.2 3241.26     232 3238.82   277.7 3234.86
   320.2 3237.54   346.4 3229.54   362.7 3228.96   388.8 3228.21   398.6  3228.7
   421.5 3232.77   434.6 3232.75   454.2 3237.83   506.5 3240.51   535.9 3243.51
   555.5 3246.92   591.4 3259.86   637.2 3274.33   722.1 3307.45   751.5 3316.52
#Mann= 5 ,-1 , 0
       0     .12       0   97.47    .016       0  130.06     .12       0
   362.7     .04       0   398.6     .12       0
Bank Sta=362.7,398.6
XS Rating Curve= 0 ,0
Exp/Cntr=0.3,0.1

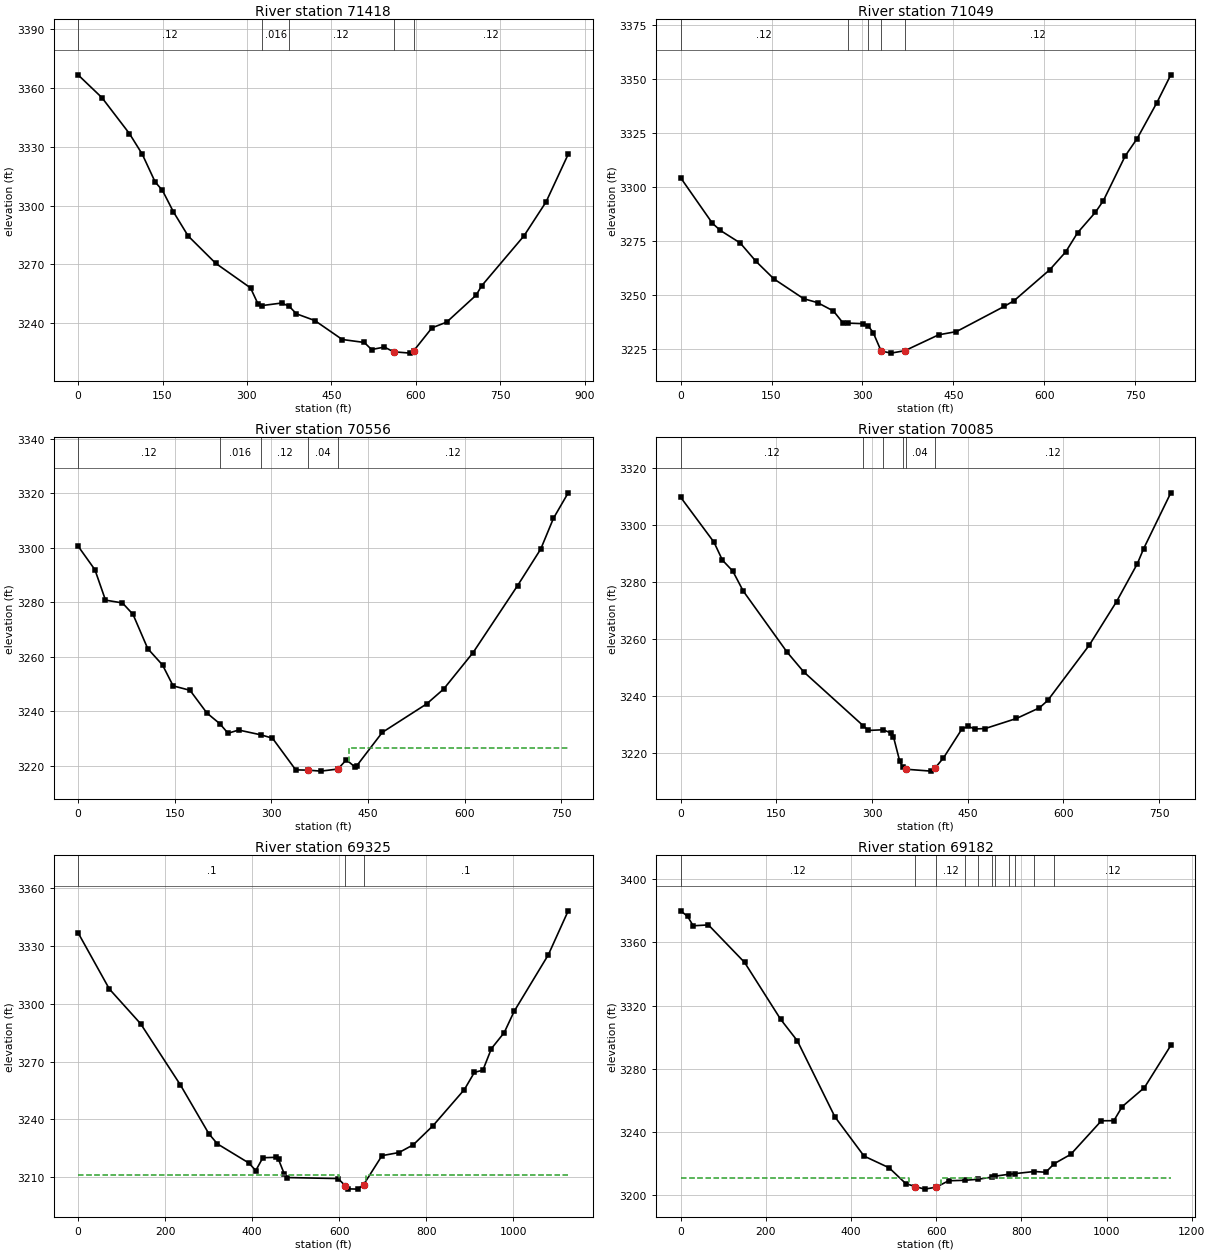
Type RM Length L Ch R = 1 ,71418   ,375.5,368.1,354.3
XS GIS Cut Line= 4
      2142571.67       442763.27     2142980.906      443012.245
     2143072.483      443158.196     2143215.572       443324.18
#Sta/Elev= 30
       0 3366.66    42.4 3355.02    91.2  3336.7     114  3326.2   136.9 3312.02
   149.9  3307.7   169.4 3296.75   195.5 3284.48   244.4 3270.54   306.3 3257.98
   319.4 3249.92  326.71 3248.96   361.7 3250.27  374.98 3248.59   387.8 3244.77
   420.4 3241.34   469.2 3231.66   508.3 3230.15   521.3 3226.54     544  3227.8
   560.3  3225.4   589.6 3224.71   596.1  3225.9   628.6 3237.62   654.6 3240.51
   706.9 3254.25   716.7 3259.01     792 3284.54   831.2 3301.85   870.5 3326.16
#Mann= 5 ,-1 , 0
       0     .12       0  326.71    .016       0  374.98     .12       0
   560.3     .04       0   596.1     .12       0
Bank Sta=560.3,596.1
XS Rating Curve= 0 ,0
Exp/Cntr=0.3,0.1

Type RM Length L Ch R = 1 ,71049   ,492.1,493.2,488
XS GIS Cut Line= 2
     2142440.028      443161.058     2143158.336       443533.09
#Sta/Elev= 30
       0  3304.3    52.4 3283.18    65.5 3279.86    98.2 3274.04   124.4 3265.48
   153.9 3257.35     203 3248.16     226 3246.33   252.2 3242.44   268.6 3236.68
  276.19 3236.83   301.3 3236.57  309.45 3235.57   317.7 3232.47   330.8  3223.9
   347.2  3222.9   370.1 3224.04   425.8  3231.4   455.2  3232.9   533.8 3244.56
   550.2 3247.23   609.2 3261.62   635.4 3269.86     655 3278.75   684.5 3288.29
   697.6 3293.66   733.6 3314.39   753.3 3322.48     786  3339.2   808.9 3352.08
#Mann= 5 ,-1 , 0
       0     .12       0  276.19    .016       0  309.45     .12       0
   330.8     .04       0   370.1     .12       0
Bank Sta=330.8,370.1
XS Rating Curve= 0 ,0
Exp/Cntr=0.3,0.1

Type RM Length L Ch R = 1 ,70556   ,472,471,469.7
XS GIS Cut Line= 2
     2142245.427      443638.976     2142949.426      443928.017
#Sta/Elev= 30
       0 3300.56    26.2 3291.88    42.6 3280.73    68.9  3279.7    85.3 3275.52
   108.2 3262.94   131.2 3256.92   147.6 3249.27   173.8 3247.65   200.1  3239.3
  220.05  3235.4   232.9 3231.88   249.3 3233.07  283.91  3231.3   301.8 3230.09
   337.9 3218.46   357.6 3218.34   376.9 3217.99   403.5 3218.76   416.6 3222.17
   429.7 3219.53     433 3220.05   472.4 3232.21   541.2 3242.65   567.5 3248.07
   613.4 3261.51   682.3 3286.02   718.4 3299.49   738.1 3310.76     761  3320.1
#Mann= 5 ,-1 , 0
       0     .12       0  220.05    .016       0  283.91     .12       0
   357.6     .04       0   403.5     .12       0
#XS Ineff= 2 , 0
                          420.12         3226.39
Permanent Ineff=
       F       F
Bank Sta=357.6,403.5
XS Rating Curve= 0 ,0
Exp/Cntr=0.3,0.1

Type RM Length L Ch R = 1 ,70085   ,732.5,760.6,791.3
XS GIS Cut Line= 2
     2142030.793      444068.244     2142757.686       444317.22
#Sta/Elev= 30
       0 3309.61    52.3 3293.83    65.4 3287.58    81.7 3283.72    98.1 3276.73
   166.8 3255.31   192.9 3248.38  285.94 3229.54   294.3 3227.84  317.16 3228.07
   330.2 3226.92   333.5  3225.7   343.3 3217.18  348.38 3214.87   353.1 3214.24
   392.4 3213.57   398.3 3214.52     412  3218.2   441.4  3228.5   451.2 3229.23
     461 3228.36   477.4  3228.5   526.4 3232.03   562.4 3235.76   575.4 3238.34
   640.8 3257.82   683.3    3273     716 3286.33   725.8 3291.58   768.4 3311.16
#Mann= 6 ,-1 , 0
       0     .12       0  285.94     .08       0  317.16    .016       0
  348.38     .12       0   353.1     .04       0   398.3     .12       0
Bank Sta=353.1,398.3
XS Rating Curve= 0 ,0
Exp/Cntr=0.5,0.3

Type RM Length L Ch R = 1 ,69325   ,146.7,143.1,141.5
XS GIS Cut Line= 4
     2141870.533      444440.276     2142319.833      444643.463
     2142299.801      444886.715     2142580.256      445155.723
#Sta/Elev= 30
       0 3336.81    71.8 3307.65   143.7 3289.61   235.1 3257.87   300.4 3232.58
     320 3227.31   391.9 3217.44   408.2 3213.49   424.5 3220.12   453.9 3220.33
   460.4 3219.27   473.5 3211.81     480 3209.85   597.2 3209.32   613.5 3205.66
     620 3203.98   642.8 3203.84   655.8 3206.14   698.1  3221.2   737.2 3222.82
   769.8  3226.8   815.6 3236.81   887.4  3255.5   910.3 3264.38   929.9 3265.54
   949.4 3276.72   978.8    3285  1001.7 3296.06  1080.1 3325.34  1125.8 3348.16
#Mann= 3 , 0 , 0
       0      .1       0   613.5     .04       0   655.8      .1       0
#XS Ineff= 2 , 0
          600.34 3211.06  661.46         3211.26
Permanent Ineff=
       F       F
Bank Sta=613.5,655.8
XS Rating Curve= 0 ,0
Exp/Cntr=0.5,0.3

Type RM Length L Ch R = 1 ,69182   ,742.5,708.4,677
XS GIS Cut Line= 4
     2141718.858      444460.309     2142165.297      444683.528
     2142168.159      444898.162     2142445.752      445235.853
#Sta/Elev= 30
       0 3380.04    16.3 3376.54    29.4 3370.55    65.2 3371.11   150.1 3347.34
   234.9 3311.22     274 3297.64   362.1 3249.48   430.6 3224.56   489.4 3217.15
   528.4 3207.16   551.2 3205.18   573.2 3203.61     600 3204.86   629.2 3208.91
  668.55 3209.22  698.09 3209.85  731.71 3211.26  737.42 3211.79  769.94    3213
  783.93 3213.41  830.45 3214.78   857.3  3214.3  876.96 3219.71     916 3225.66
   987.8 3246.92  1017.2 3247.02  1036.8 3255.91    1089    3268  1150.9 3294.72
#Mann= 11 ,-1 , 0
       0     .12       0   551.2     .04       0     600     .12       0
  668.55     .06       0  698.09     .12       0  731.71     .06       0
  737.42     .12       0  769.94     .06       0  783.93     .08       0
  830.45    .016       0  876.96     .12       0
#XS Ineff= 2 , 0
          535.86 3210.61  612.03         3210.93
Permanent Ineff=
       F       F
Bank Sta=551.2,600
XS Rating Curve= 0 ,0
Exp/Cntr=0.5,0.3