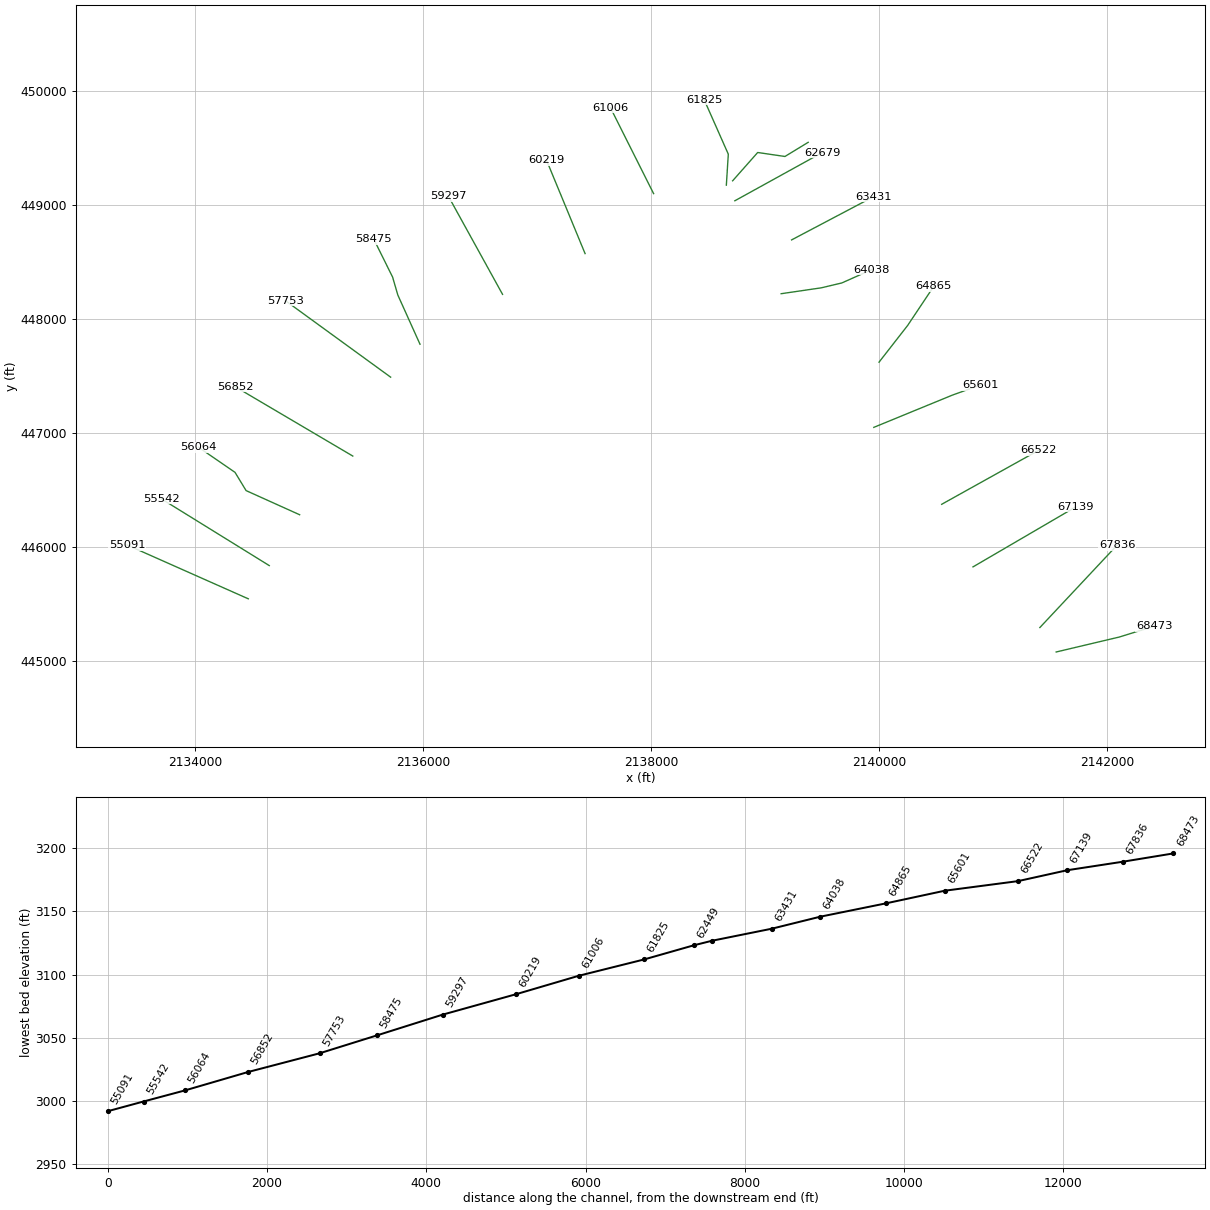
HEC-RAS study NFKCHERRYRV.prj: NFKCHERRYRV

--- NFKCHERRYRV.g01 (geometry) --- (continued)

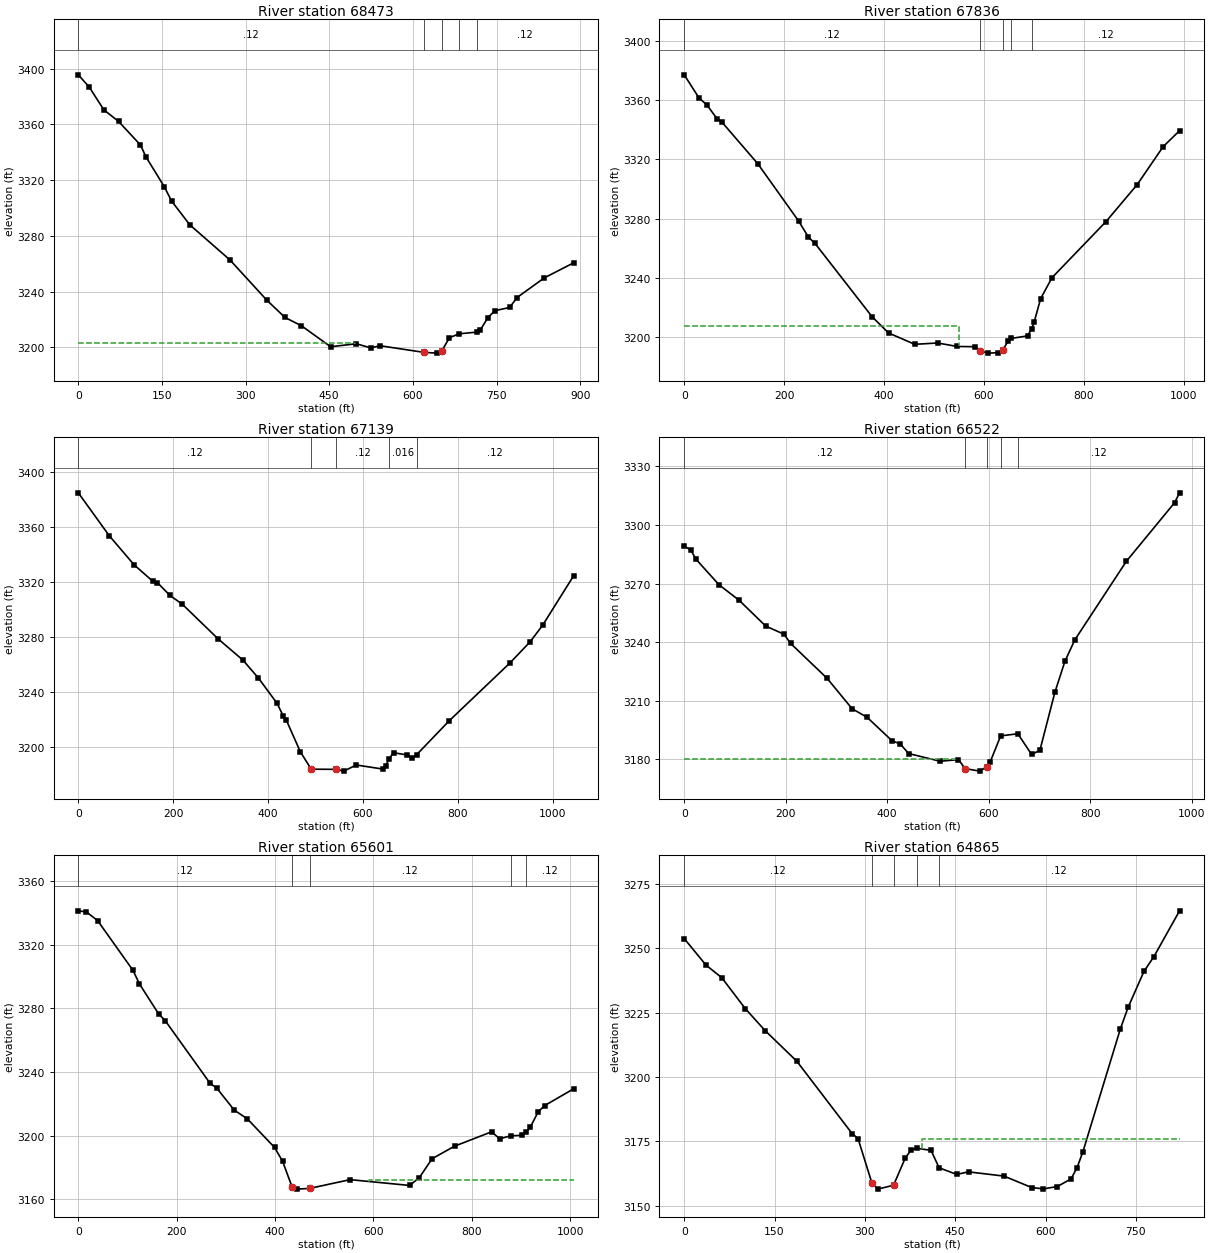
Type RM Length L Ch R = 1 ,68473   ,626.2,637.2,645.8
XS GIS Cut Line= 3
     2141550.013      445075.593     2142105.199      445207.235
     2142408.549      445301.674
#Sta/Elev= 30
       0 3395.52    19.7 3386.68    45.9 3370.35    72.1 3362.15   111.5 3345.18
   121.3 3336.69   154.1 3315.35   167.2 3305.04     200 3287.91   272.2 3262.65
   337.8 3233.98   370.6  3221.5   400.1 3215.54   452.5 3200.47   498.4 3202.62
   524.7 3199.65   541.1  3201.2   619.7 3196.46   642.6  3195.9  652.24 3197.72
   665.6    3207  683.17 3209.76  714.11 3210.96   721.2 3212.57   734.4 3221.37
   747.4  3226.4   773.6 3228.64   786.8 3235.77   835.9 3249.93   888.3 3260.67
#Mann= 5 ,-1 , 0
       0     .12       0   619.7     .04       0  652.24     .08       0
  683.17    .016       0  714.11     .12       0
#XS Ineff= 2 , 0
          496.18 3202.89
Permanent Ineff=
       F       F
Bank Sta=619.7,652.24
XS Rating Curve= 0 ,0
Exp/Cntr=0.3,0.1

Type RM Length L Ch R = 1 ,67836   ,695.8,697.3,678.6
XS GIS Cut Line= 2
     2141406.924      445290.227     2142085.167      446014.258
#Sta/Elev= 30
       0    3377    29.5 3361.46    45.8 3356.54    65.5 3347.47    75.3 3345.19
   147.3 3317.06   229.2 3278.36   248.8 3267.53   261.9 3263.33   376.5 3213.76
   409.3  3202.9   461.7 3195.26   507.5 3196.14   546.8  3193.8   582.8 3193.63
   592.6 3190.78     609 3189.31   628.6 3189.62   638.5 3191.69   648.3 3197.19
  655.41 3199.24   687.6 3200.94  695.88  3205.7   700.7 3210.01   713.8 3226.04
   736.7 3240.22   844.8 3278.03     907 3302.86   959.3 3328.59   992.1 3339.31
#Mann= 5 ,-1 , 0
       0     .12       0   592.6     .04       0   638.5     .12       0
  655.41    .016       0  695.88     .12       0
#XS Ineff= 2 , 0
          550.59 3207.32
Permanent Ineff=
       F       F
Bank Sta=592.6,638.5
XS Rating Curve= 0 ,0
Exp/Cntr=0.3,0.1

Type RM Length L Ch R = 1 ,67139   ,615.2,616.5,612.7
XS GIS Cut Line= 2
     2140820.258      445822.519      2141721.72      446349.087
#Sta/Elev= 30
       0 3384.57    65.4 3353.36   117.8 3332.25   157.1 3320.37   166.9 3319.33
   193.1 3310.13   219.3 3303.68   294.5 3278.63   346.9 3263.18   379.6 3250.17
   418.9  3231.8     432  3222.6   438.5 3219.55     468 3196.62   490.9    3184
   543.3 3183.87   559.6 3182.59   585.8 3187.04   641.4 3184.12     648  3186.4
  654.84 3191.49   664.4 3195.94   693.8  3194.3   703.6 3192.16  712.84 3194.44
   782.2 3219.28   909.8  3261.1   952.4 3276.49   978.5 3288.37    1044 3324.39
#Mann= 5 ,-1 , 0
       0     .12       0   490.9     .04       0   543.3     .12       0
  654.84    .016       0  712.84     .12       0
Bank Sta=490.9,543.3
XS Rating Curve= 0 ,0
Exp/Cntr=0.3,0.1

Type RM Length L Ch R = 1 ,66522   ,918.9,921.6,917.9
XS GIS Cut Line= 2
     2140545.526      446371.982     2141398.338      446847.038
#Sta/Elev= 30
       0 3289.22    13.1  3287.1    22.9 3282.54    68.8 3269.33   108.1 3261.47
   160.5 3248.26   196.6 3244.07   209.6 3239.38   281.7 3221.46   330.9  3205.9
   360.3 3201.56   409.5 3189.53   425.9 3187.88   442.2 3182.98   504.5 3179.04
   540.5 3179.89   553.6 3175.27   582.6 3173.98   596.2 3176.19   602.8 3178.56
  623.64 3192.02  657.45 3193.11   684.6 3182.52     701 3184.66   730.5 3214.34
   750.2 3230.15   769.8 3241.19   871.4 3281.42   966.4  3311.4   976.2 3316.46
#Mann= 5 ,-1 , 0
       0     .12       0   553.6     .04       0   596.2     .08       0
  623.64    .016       0  657.45     .12       0
#XS Ineff= 2 , 0
          533.13 3180.29
Permanent Ineff=
       F       F
Bank Sta=553.6,596.2
XS Rating Curve= 0 ,0
Exp/Cntr=0.3,0.1

Type RM Length L Ch R = 1 ,65601   ,723.2,735.9,741.1
XS GIS Cut Line= 3
     2139950.275      447047.363     2140639.965       447330.68
     2140886.079      447419.395
#Sta/Elev= 30
       0 3341.21    16.4 3340.54    39.2 3335.09   111.2 3303.81   124.3 3295.28
   163.5 3276.38   176.6 3272.26   268.2 3232.74   281.2 3229.96   317.2 3215.98
   343.4  3210.6     399 3192.57   415.3 3183.93   434.9 3167.56   444.8 3166.37
   470.9 3166.85   552.7 3172.33   673.7 3168.68   693.3 3173.53   719.4 3185.48
   765.2 3193.37   840.4 3202.38   856.8 3197.99     879 3199.85   902.6 3200.19
   910.4 3202.11   918.9 3205.18   935.3 3215.03   948.4 3218.88  1007.2 3229.39
#Mann= 5 ,-1 , 0
       0     .12       0   434.9     .04       0   470.9     .12       0
     879    .016       0   910.4     .12       0
#XS Ineff= 2 , 0
                          591.92         3171.88
Permanent Ineff=
       F       F
Bank Sta=434.9,470.9
XS Rating Curve= 0 ,0
Exp/Cntr=0.3,0.1

Type RM Length L Ch R = 1 ,64865   ,845.4,826.6,798.4
XS GIS Cut Line= 3
     2139996.063       447619.72     2140247.901      447943.102
     2140476.843      448286.516
#Sta/Elev= 30
       0 3253.74    36.1 3243.45    62.3 3238.55   101.6 3226.47   134.4 3217.97
   186.9 3206.11   278.7 3178.01   288.6 3176.06   311.5  3158.9   321.3  3156.4
   347.6  3157.9   367.2 3168.55   377.1 3171.66  386.55 3172.26   409.9 3171.47
  423.26 3164.69   452.5 3162.12   472.1 3163.11   531.1 3161.46   576.9 3157.03
   596.6  3156.5   619.5  3157.4   642.4 3160.38   652.3 3164.68   662.1 3170.93
   724.3 3218.66   737.4 3227.18   763.6 3241.04     780 3246.73   822.6 3264.52
#Mann= 5 ,-1 , 0
       0     .12       0   311.5     .04       0   347.6     .12       0
  386.55    .016       0  423.26     .12       0
#XS Ineff= 2 , 0
                          395.14         3175.97
Permanent Ineff=
       F       F
Bank Sta=311.5,347.6
XS Rating Curve= 0 ,0
Exp/Cntr=0.3,0.1

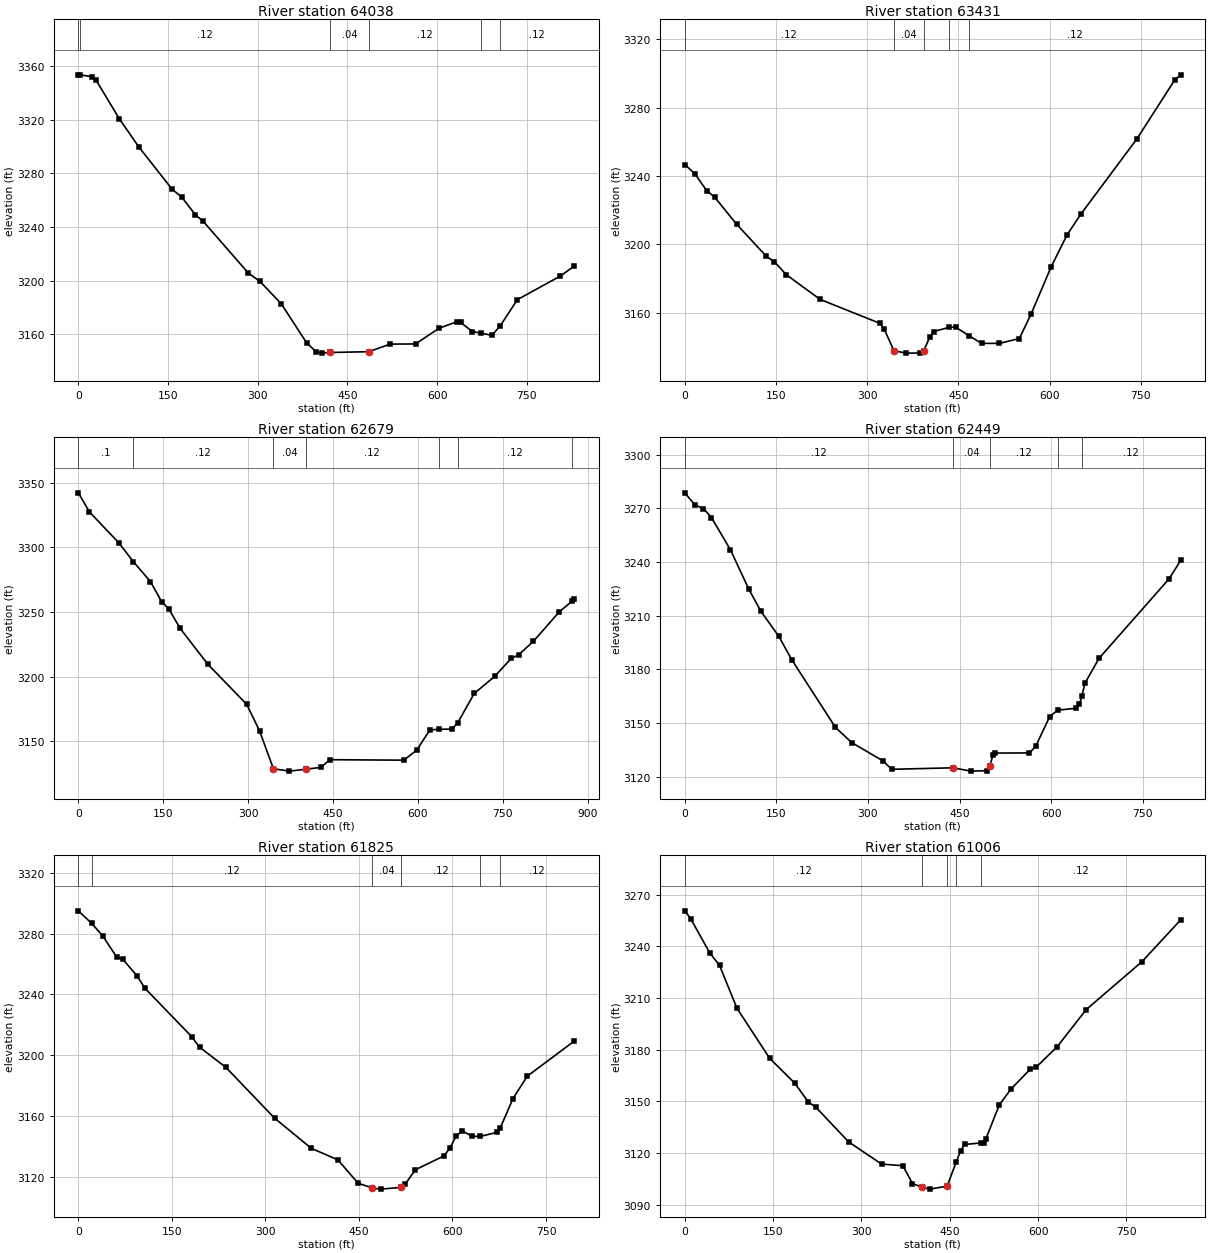
Type RM Length L Ch R = 1 ,64038   ,590.2,607,601.8
XS GIS Cut Line= 4
     2139137.528      448220.695     2139489.527      448272.207
      2139669.82      448315.134     2139933.104      448432.467
#Sta/Elev= 30
       0 3353.51    3.47 3353.37    22.8 3352.21    29.4 3349.75    68.5 3320.74
   101.2 3299.67   156.7 3268.23     173 3262.22   195.8 3249.03   208.9 3244.17
     284 3205.71   303.5 3199.43   339.4 3182.69   381.8 3153.53     398  3146.7
   407.8 3145.82   420.8 3146.29   485.8 3146.89   521.6 3152.55     564 3152.67
   603.3 3164.37   632.8 3169.19   639.4  3168.7     659 3161.94  673.49 3160.77
   691.8 3159.08  705.83 3166.26   734.3 3185.73   806.4 3203.39   829.3 3210.76
#Mann= 6 ,-1 , 0
       0      .1       0    3.47     .12       0   420.8     .04       0
   485.8     .12       0  673.49    .016       0  705.83     .12       0
Bank Sta=420.8,485.8
XS Rating Curve= 0 ,0
Exp/Cntr=0.3,0.1

Type RM Length L Ch R = 1 ,63431   ,731.1,751.5,727.7
XS GIS Cut Line= 2
     2139229.105       448692.89     2139950.275      449073.507
#Sta/Elev= 30
       0 3246.68    16.4  3241.4      36 3231.44    49.1 3227.64    85.2 3211.78
   134.3 3192.91   147.4 3189.83     167 3182.21   222.7 3167.76   320.9 3153.77
   327.5  3150.7   343.9 3137.82   363.5 3136.35   386.4 3136.39     393 3137.85
   402.8 3145.62   409.4 3148.99   434.7 3151.44   445.4 3151.57   468.1 3146.38
     488 3142.06   517.4 3142.05   550.2  3144.9   569.8 3159.46   602.6 3186.96
   628.8 3205.64   651.7 3217.86   743.4 3261.67   805.6 3296.13   815.4  3299.2
#Mann= 5 ,-1 , 0
       0     .12       0   343.9     .04       0     393     .08       0
   434.7    .016       0   468.1     .12       0
#XS Ineff= 2 , 0
                          438.67         3151.21
Permanent Ineff=
       F       F
Bank Sta=343.9,393
XS Rating Curve= 0 ,0
Exp/Cntr=0.3,0.1

Type RM Length L Ch R = 1 ,62679   ,242.9,230.3,206.2
XS GIS Cut Line= 2
     2138731.154      449036.304     2139498.113      449459.848
#Sta/Elev= 30
       0 3342.23    19.6 3327.44    71.9 3303.34   97.01 3289.06   127.5 3273.48
   147.1 3258.07   160.2 3252.16   179.8 3237.34   228.8 3209.53   297.5 3178.52
   320.4 3157.73  344.66 3128.63   372.7  3126.8   402.1 3128.27   428.3 3129.68
   444.6 3135.65   575.4 3135.28   598.3 3143.25   621.1 3158.68  636.86 3159.15
   660.4 3159.36   670.6 3164.39   699.6 3186.95   735.6 3200.11     765 3214.07
   778.1 3216.85   804.2 3227.34     850 3250.19  873.04 3258.58   876.1 3259.79
#Mann= 7 ,-1 , 0
       0      .1       0   97.01     .12       0  344.66     .04       0
   402.1     .12       0  636.86    .016       0   670.6     .12       0
  873.04      .1       0
Bank Sta=344.66,402.1
XS Rating Curve= 0 ,0
Exp/Cntr=0.3,0.1

Type RM Length L Ch R = 1 ,62449   ,591.9,623.8,700.4
XS GIS Cut Line= 4
2138711.90933595449211.814095174 2138931.7427033449460.321380011
2139170.69201565449425.2754808672139374.59542884449549.529123285
#Sta/Elev= 30
       0 3278.73    16.6 3271.97    30.6 3269.91    43.7 3264.92    74.8 3246.83
     105  3224.8   124.7 3212.48   153.8 3198.61   175.1  3185.5   246.7 3147.64
   273.3 3139.15   324.1 3128.98     339  3124.2   439.5 3125.03   468.3 3123.17
   494.9 3123.41   499.3 3125.95   504.8 3132.09   508.1 3133.26   564.5 3133.35
   574.6 3136.95   597.7 3153.69   610.6 3157.24   640.8 3158.31   646.4 3160.49
   650.3 3164.95   655.3 3172.28   678.4 3186.19   793.6 3230.81   812.1 3240.94
#Mann= 5 ,-1 , 0
       0     .12       0   439.5     .04       0   499.3     .12       0
   610.6    .016       0   650.3     .12       0
Bank Sta=439.5,499.3
XS Rating Curve= 0 ,0
Exp/Cntr(USF)=0,0
Exp/Cntr=0.3,0.1

Type RM Length L Ch R = 1 ,61825   ,809.6,819.7,803.7
XS GIS Cut Line= 3
     2138656.748       449173.67     2138673.918      449445.539
     2138462.146      449923.457
#Sta/Elev= 30
       0 3294.93   21.14  3286.8    38.9 3278.58    61.6 3264.46    71.4 3263.05
      94 3252.27     107 3243.94   181.6 3212.31   194.6 3205.21   236.7 3192.01
   314.9 3158.57   373.7  3138.8   416.2 3131.23   448.8 3115.84   471.7 3112.74
   484.8 3111.98   517.4 3113.12     524 3115.03   540.3 3124.67     586 3133.73
   595.8 3138.82   605.7 3146.74   615.5  3150.2   631.8 3146.71  644.24 3146.59
     671 3149.26  676.55  3152.1   697.1 3171.52     720 3186.22   795.2 3209.25
#Mann= 6 ,-1 , 0
       0      .1       0   21.14     .12       0   471.7     .04       0
   517.4     .12       0  644.24    .016       0  676.55     .12       0
Bank Sta=471.7,517.4
XS Rating Curve= 0 ,0
Exp/Cntr=0.3,0.1

Type RM Length L Ch R = 1 ,61006   ,787,786.3,777.4
XS GIS Cut Line= 2
      2138018.57      449099.263     2137640.814      449851.913
#Sta/Elev= 30
       0 3260.61     9.8 3256.14    42.6 3236.09      59 3228.99    88.5 3204.09
   144.2 3174.98   186.8 3160.58   209.7 3149.69   222.8 3146.53   278.5 3126.42
   334.2 3113.62   370.3 3112.67   386.7 3102.34     403  3100.2   416.2 3099.08
   445.6 3100.81  460.85 3114.77   468.6 3121.48   475.1    3125  503.43 3125.91
   507.9 3126.01   511.2 3128.11   534.1 3147.94   553.8  3157.1   586.5  3168.6
   596.4 3169.72   632.4 3181.72   681.6 3203.23   776.6 3231.16   842.1 3255.31
#Mann= 5 ,-1 , 0
       0     .12       0     403     .04       0   445.6     .08       0
  460.85    .016       0  503.43     .12       0
Bank Sta=403,445.6
XS Rating Curve= 0 ,0
Exp/Cntr=0.3,0.1

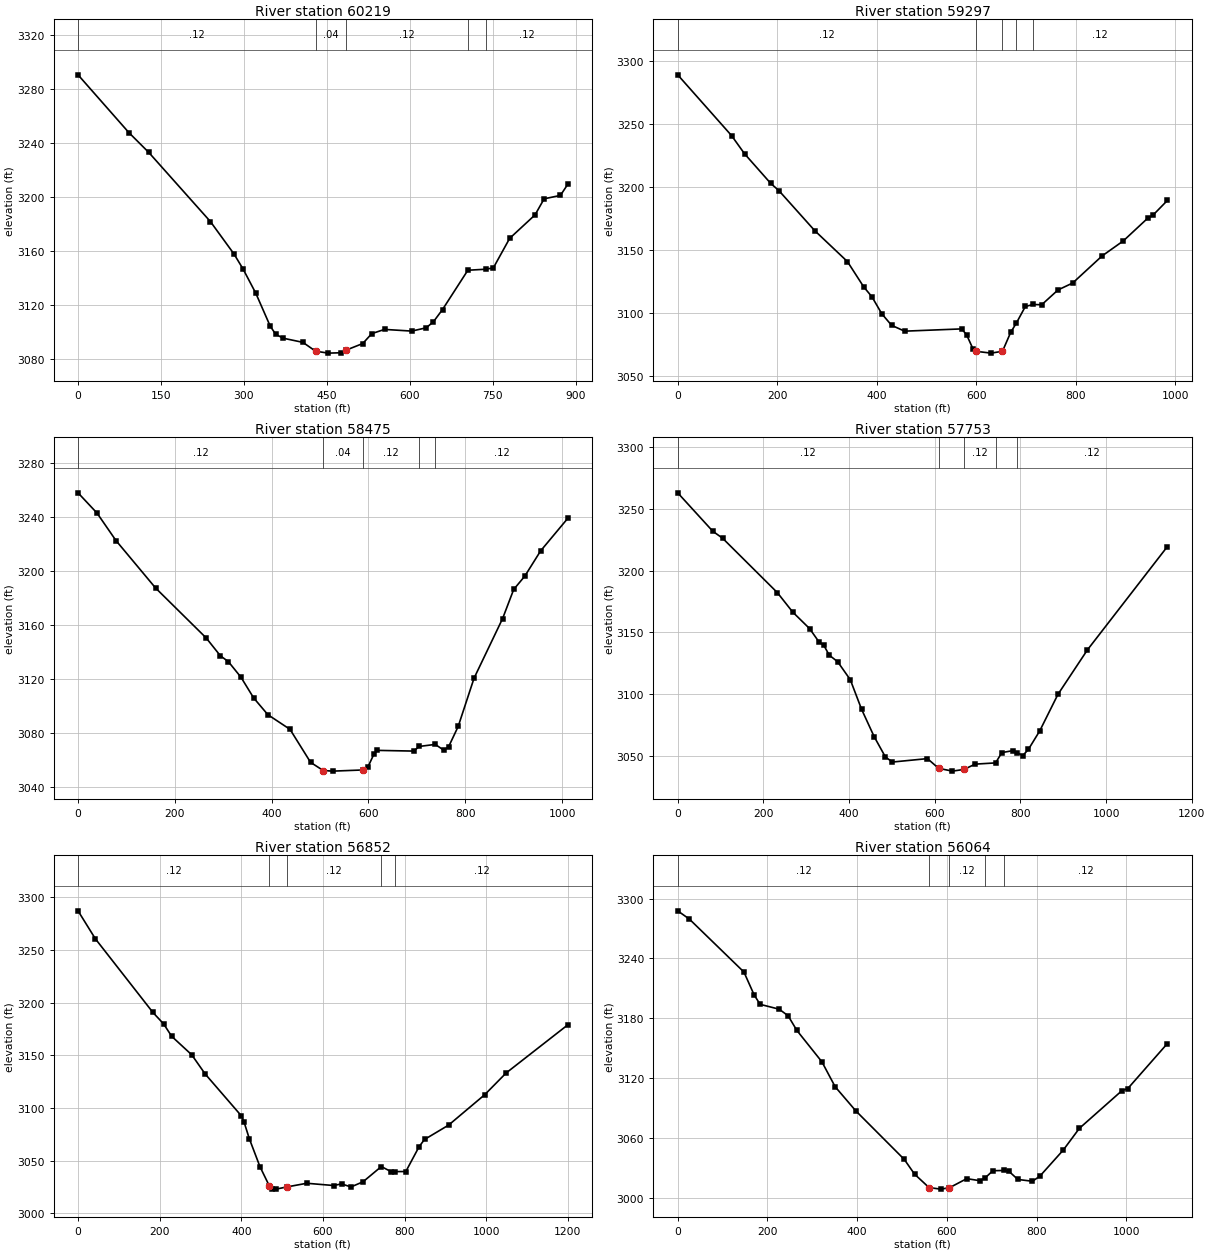
Type RM Length L Ch R = 1 ,60219   ,906.1,922.8,914.4
XS GIS Cut Line= 2
     2137417.595      448572.695     2137079.904      449391.165
#Sta/Elev= 30
       0 3290.39    91.8 3247.72   127.9 3232.99   239.4 3181.82     282 3157.87
   298.4 3146.77   321.4 3128.87   347.6 3104.41   357.4 3098.51   370.6 3095.58
   406.6 3092.48   429.6 3085.94   452.5 3084.51   475.5 3084.78   485.3 3086.82
   514.8  3091.6   531.2 3098.94   554.2 3102.06   603.4 3100.81   629.6 3103.25
   642.7 3107.74   659.1 3116.78   704.9 3145.83  736.85 3146.57     751 3147.57
   780.5 3169.42   826.4 3186.78   842.8 3198.66   872.3  3201.2   885.4 3209.32
#Mann= 5 ,-1 , 0
       0     .12       0   429.6     .04       0   485.3     .12       0
   704.9    .016       0  736.85     .12       0
Bank Sta=429.6,485.3
XS Rating Curve= 0 ,0
Exp/Cntr=0.3,0.1

Type RM Length L Ch R = 1 ,59297   ,824.6,821.8,804.3
XS GIS Cut Line= 2
     2136693.563      448214.971     2136218.507      449076.369
#Sta/Elev= 30
       0 3289.19   108.2 3240.96   134.4 3226.48   186.9 3203.03   203.3  3197.3
   275.4 3165.49     341 3140.97   373.8 3120.84   390.2 3113.05   409.9 3099.63
   429.6 3090.43   455.8 3085.76   570.6 3087.56   580.4 3082.85   593.5 3071.45
   600.1 3069.73   629.6 3068.33   652.5  3069.8   668.9 3084.76  680.44 3092.25
   698.4 3105.34  714.17 3106.94   731.2  3106.7     764 3118.46   793.5 3123.97
   852.6 3145.47   895.2 3157.39   944.4 3175.47   954.2 3177.57   983.7 3189.46
#Mann= 5 ,-1 , 0
       0     .12       0   600.1     .04       0   652.5     .12       0
  680.44    .016       0  714.17     .12       0
Bank Sta=600.1,652.5
XS Rating Curve= 0 ,0
Exp/Cntr=0.3,0.1

Type RM Length L Ch R = 1 ,58475   ,690.5,722.2,738
XS GIS Cut Line= 4
     2135969.531      447777.118      2135774.93      448209.248
     2135729.141      448366.646     2135563.158      448701.475
#Sta/Elev= 30
       0 3258.02    39.2 3243.05    78.4 3222.69   160.2 3187.57   264.7 3150.61
   294.2 3137.34   310.5 3133.08   336.6 3121.52   362.8  3106.2   392.2 3093.77
     438 3082.89   480.5 3058.46   506.7  3052.4   526.4 3051.98   588.7 3052.84
   598.5 3054.69   611.6  3064.8   618.2 3067.34   693.6 3066.82  705.04 3070.26
     738 3071.76   755.9 3067.43   765.7 3070.08   785.4 3085.07   818.2 3120.82
   877.2 3164.97   900.1  3186.5     923 3196.33   955.8 3215.09  1011.6 3239.04
#Mann= 5 ,-1 , 0
       0     .12       0   506.7     .04       0   588.7     .12       0
  705.04    .016       0     738     .12       0
Bank Sta=506.7,588.7
XS Rating Curve= 0 ,0
Exp/Cntr=0.3,0.1

Type RM Length L Ch R = 1 ,57753   ,883.2,900.8,895.6
XS GIS Cut Line= 2
     2135711.971      447488.078     2134787.614      448160.598
#Sta/Elev= 30
       0 3263.02    81.9 3231.93   104.8 3226.28   232.6 3182.26   268.6 3166.47
   307.9 3153.13   330.8 3141.88   340.6 3139.93   353.7 3131.67   373.4 3126.32
   402.9 3111.77   429.1 3087.96   458.6  3065.7   484.8 3049.29   501.1 3045.12
     583  3047.9   609.2 3040.02   641.4 3037.77   668.2 3039.14   694.4 3043.43
   742.2 3044.43   756.6 3052.75   782.8 3054.38  792.41 3052.59   805.8 3050.41
   818.8 3055.42   845.1 3070.29   887.6 3099.86   956.4 3135.87  1143.1 3219.49
#Mann= 5 ,-1 , 0
       0     .12       0   609.2     .04       0   668.2     .12       0
   742.2    .016       0  792.41     .12       0
Bank Sta=609.2,668.2
XS Rating Curve= 0 ,0
Exp/Cntr=0.3,0.1

Type RM Length L Ch R = 1 ,56852   ,792.7,787.4,771.5
XS GIS Cut Line= 2
     2135380.003      446795.526     2134346.899      447405.086
#Sta/Elev= 30
       0 3287.02    42.6 3260.41   183.5 3190.57   209.8 3179.66   229.4 3167.95
   278.6 3150.37   311.4 3132.23   399.8 3092.61   406.4 3087.01   419.5 3070.89
   445.7 3044.23   468.7 3025.92   475.2 3023.32   485.1 3022.92   511.3 3024.98
   560.4 3028.48     626 3026.35   645.6 3027.88   668.6    3025   698.1 3029.85
  743.02 3044.36   766.9  3039.5  777.31 3039.54     803 3039.63   835.7 3063.33
   848.8 3070.04   907.8 3083.68   996.3 3112.53  1048.8 3133.16  1199.5 3178.73
#Mann= 5 ,-1 , 0
       0     .12       0   468.7     .04       0   511.3     .12       0
  743.02    .016       0  777.31     .12       0
Bank Sta=468.7,511.3
XS Rating Curve= 0 ,0
Exp/Cntr=0.3,0.1

Type RM Length L Ch R = 1 ,56064   ,503.1,522.7,528.3
XS GIS Cut Line= 4
     2134913.532      446280.404       2134444.2      446492.177
     2134346.899      446652.437     2134026.379      446872.794
#Sta/Elev= 30
       0 3287.74    26.2 3279.36   147.6 3226.31   170.5 3203.22   183.7 3193.89
   226.3    3189     246 3182.44   265.6 3167.71   321.4 3136.21   350.9 3111.21
   396.8 3087.06   505.1  3038.2   527.8 3023.51   560.2 3009.99     586 3008.44
   605.4 3009.77   644.2 3018.96   673.3 3016.91  684.66 3019.48   702.4 3026.92
  727.07 3027.16   738.3 3026.31     758 3018.16   790.6 3016.33     807 3021.38
   859.3 3047.64   895.2 3069.44     990 3107.24  1003.1 3109.35  1091.3 3154.52
#Mann= 5 ,-1 , 0
       0     .12       0   560.2     .04       0   605.4     .12       0
  684.66    .016       0  727.07     .12       0
Bank Sta=560.2,605.4
XS Rating Curve= 0 ,0
Exp/Cntr=0.3,0.1

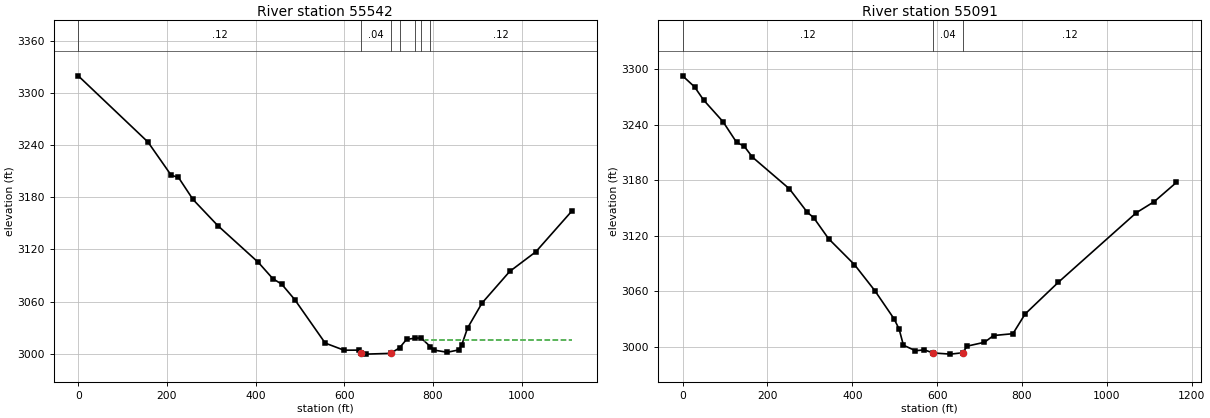
Type RM Length L Ch R = 1 ,55542   ,440.1,450.3,450
XS GIS Cut Line= 2
     2134647.386      445833.966     2133700.135      446420.632
#Sta/Elev= 30
       0 3319.58   157.3 3243.45   209.7 3205.27   226.1 3202.77   258.9 3177.42
   314.6 3147.49   406.4 3105.04   439.1 3086.31   458.8 3080.16   488.3 3062.41
   557.1 3012.32   599.7 3004.13   632.5 3004.24     639 3001.04   648.9 2999.63
   704.6 3000.51   724.8 3006.86   740.6 3016.53  759.54    3018  773.38  3018.2
  794.28 3008.29   802.9 3004.26   832.4 3001.76   858.6  3004.5   865.2 3010.26
   878.3 3029.66     911 3058.39   973.3 3094.66  1032.3 3117.28  1114.2  3164.5
#Mann= 7 ,-1 , 0
       0     .12       0     639     .04       0   704.6     .12       0
   724.8    .016       0  759.54     .08       0  773.38     .06       0
  794.28     .12       0
#XS Ineff= 2 , 0
                          782.14         3015.33
Permanent Ineff=
       F       F
Bank Sta=639,704.6
XS Rating Curve= 0 ,0
Exp/Cntr=0.3,0.1

Type RM Length L Ch R = 1 ,55091   ,593.7,600.9,597.3
XS GIS Cut Line= 2
2134463.34333333445542.342057198 2133399.5584919446015.135320056
#Sta/Elev= 30
       0 3292.75    28.1 3280.86    49.7 3266.51    95.2 3243.23   127.5 3220.69
   144.9 3216.86   164.6 3204.88   251.8 3170.58     294 3145.21   308.9 3139.48
   344.1  3116.7   405.2 3088.62   453.1 3060.56   498.5 3030.04   510.3 3019.07
   520.5 3001.59   548.8 2995.63   569.9  2996.5   590.82993.186   631.4 2991.93
   660.1 2993.38   670.8 3000.58   711.6 3004.75   732.9 3012.03   778.6 3014.01
   807.3 3035.28   885.6 3069.57  1069.5 3144.79  1111.8  3156.8  1164.1 3177.58
#Mann= 3 , 0 , 0
       0     .12       0   590.8     .04       0   660.1     .12       0
Bank Sta=590.8,660.1
XS Rating Curve= 0 ,0
Exp/Cntr(USF)=0,0
Exp/Cntr=0.3,0.1