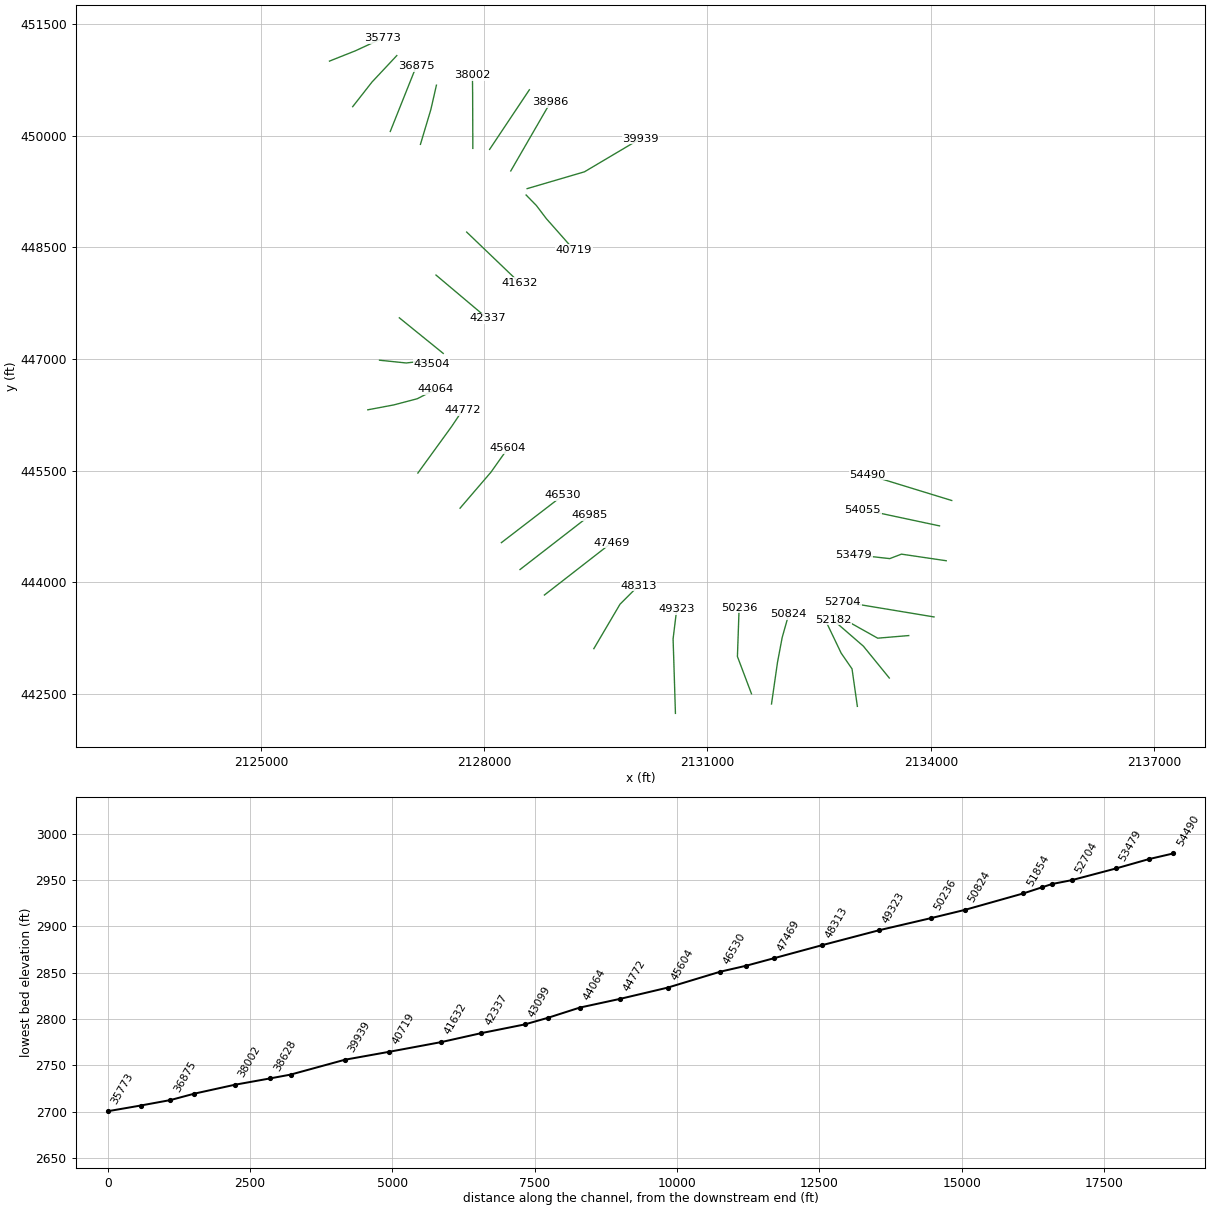
HEC-RAS study NFKCHERRYRV.prj: NFKCHERRYRV

--- NFKCHERRYRV.g01 (geometry) --- (continued)

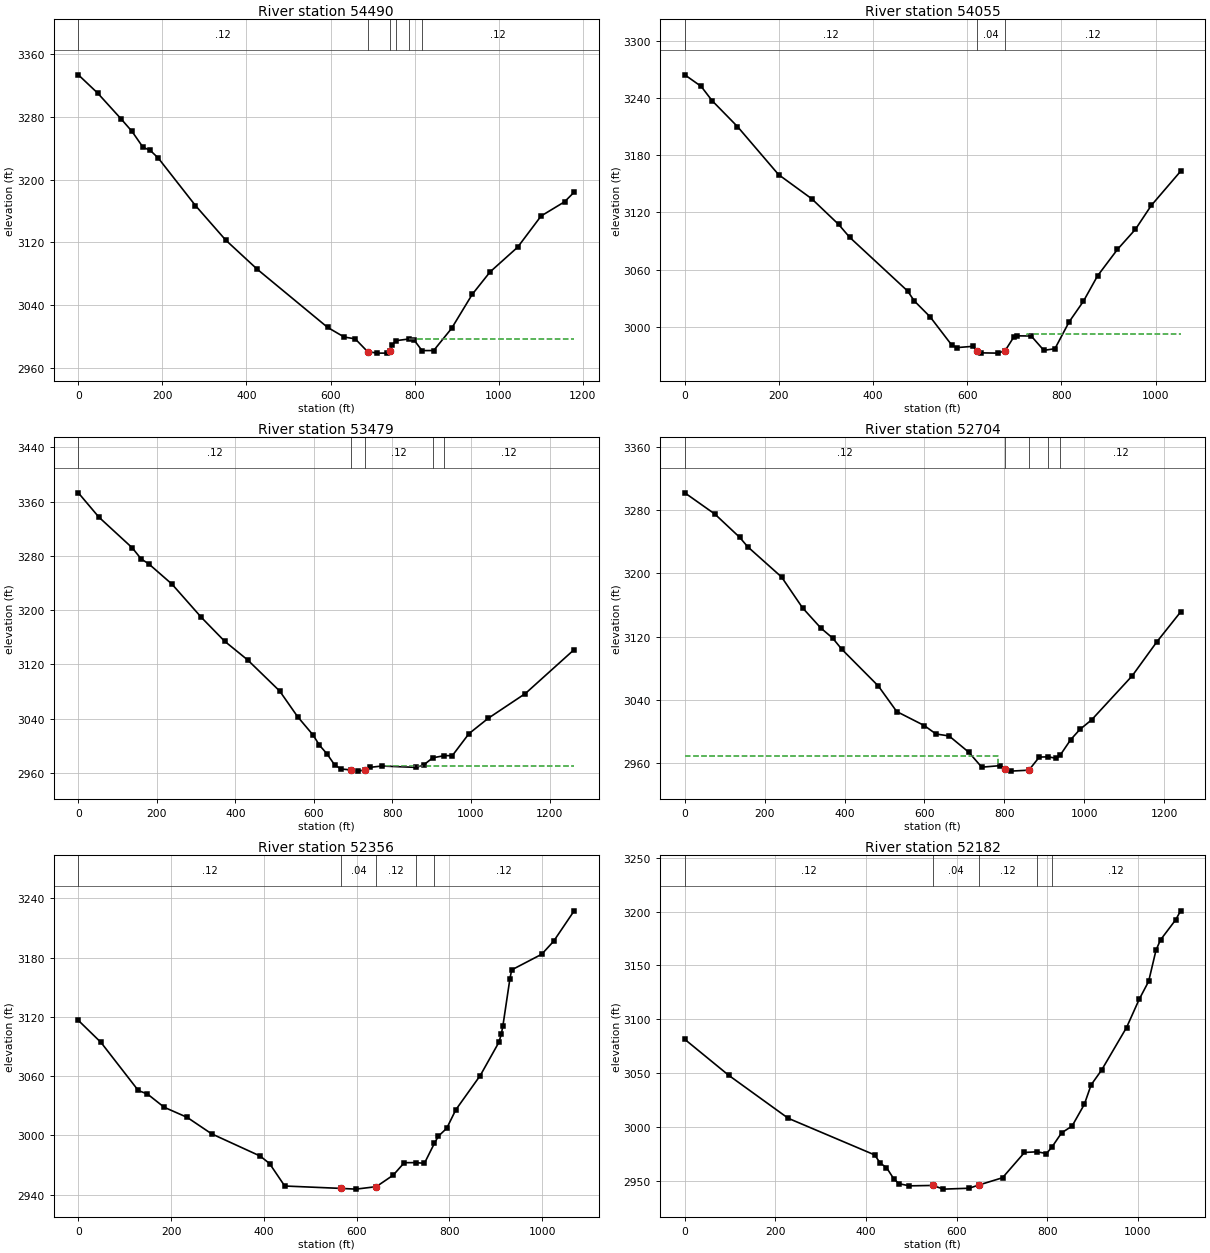
Type RM Length L Ch R = 1 ,54490   ,430.5,435.8,435.7
XS GIS Cut Line= 2
     2134281.078      445098.487     2133153.534      445444.763
#Sta/Elev= 30
       0 3334.03    45.9 3310.74   101.6 3277.79   127.8 3261.69     154 3241.37
   170.4 3237.85     190 3227.82   278.5 3167.13   350.6 3122.95   425.9 3085.58
     593 3011.46   632.4 2999.15   658.6 2996.84     688 2980.53     711  2978.6
   733.9 2978.63   740.5 2981.72     747 2989.45  755.77 2994.51  786.67 2996.69
   799.4 2994.83  817.56 2981.83   845.3  2981.9   887.9 3010.17   937.1 3053.72
   979.6 3082.38  1045.2 3113.96  1100.9 3153.76  1156.6 3171.84  1179.5 3184.19
#Mann= 6 ,-1 , 0
       0     .12       0     688     .04       0   740.5     .12       0
  755.77     .08       0  786.67    .016       0  817.56     .12       0
#XS Ineff= 2 , 0
                          787.56         2997.24
Permanent Ineff=
       F       F
Bank Sta=688,740.5
XS Rating Curve= 0 ,0
Exp/Cntr=0.3,0.1

Type RM Length L Ch R = 1 ,54055   ,557.2,575.3,582.8
XS GIS Cut Line= 2
2134117.19112302 444757.167531382133087.17722894444976.678689136
#Sta/Elev= 30
       0 3264.11    34.7 3252.02    57.9 3237.06   111.9 3209.85   199.1 3159.53
   269.5 3134.22   326.6 3107.36     350 3093.88   473.1 3037.55   487.6 3027.01
   521.1 3010.38   567.1 2980.72   578.1 2978.18   611.7 2979.49     6212975.043
   628.4 2972.66   665.3 2972.38   680.5 2975.07   698.9 2989.37   705.4  2990.5
   735.8 2990.34   762.6 2975.31   786.1 2976.97   816.3 3005.16   846.6  3026.7
   876.7 3053.41     919 3081.14   957.2 3102.23   990.7 3127.14  1053.1 3163.05
#Mann= 3 , 0 , 0
       0     .12       0     621     .04       0   680.5     .12       0
#XS Ineff= 2 , 0
                          726.52         2991.95
Permanent Ineff=
       F       F
Bank Sta=621,680.5
XS Rating Curve= 0 ,0
Exp/Cntr(USF)=0,0
Exp/Cntr=0.3,0.1

Type RM Length L Ch R = 1 ,53479   ,780,775.1,775.8
XS GIS Cut Line= 4
     2134206.671      444288.602     2133605.696      444377.317
     2133448.298       444317.22     2132964.656      444371.594
#Sta/Elev= 30
       0 3373.08    52.3 3337.22   137.2 3291.94     160 3275.53   179.6 3268.08
   238.4 3238.36   313.5 3189.11   372.3 3154.19   431.1 3126.49   512.8 3080.53
   558.5 3042.61   597.7 3015.69     614 3000.63   633.4  2987.7   652.8 2971.44
     669 2965.53     695 2964.04   711.2 2962.33   730.6 2964.03   743.6 2967.95
   772.7 2969.85   860.9 2967.86   880.5 2971.94  902.74 2982.04  932.46 2985.18
   952.4 2985.17   994.8 3017.64  1043.8 3040.29  1138.5 3076.88  1262.7 3141.69
#Mann= 5 ,-1 , 0
       0     .12       0     695     .04       0   730.6     .12       0
  902.74    .016       0  932.46     .12       0
#XS Ineff= 2 , 0
                          781.91         2970.35
Permanent Ineff=
       F       F
Bank Sta=695,730.6
XS Rating Curve= 0 ,0
Exp/Cntr=0.3,0.1

Type RM Length L Ch R = 1 ,52704   ,360.6,348.6,335.6
XS GIS Cut Line= 2
      2134043.55       443533.09     2132818.705      443736.277
#Sta/Elev= 30
       0 3301.72    75.4 3274.79   137.6 3245.36   157.2 3233.64   242.4 3195.19
   294.8  3156.3   340.7 3130.69   370.2 3118.01   393.1 3103.91   484.8  3057.3
   530.7 3025.09   599.5 3007.42     629 2996.71   661.7 2994.26   710.9 2973.74
   743.6 2954.73   789.5 2956.68   802.6  2951.8   815.7 2949.74   861.6 2950.96
   887.8 2967.54  910.73 2967.78   930.4 2965.94  940.67 2970.39   966.4  2989.6
   989.3 3002.45  1018.8 3014.63  1120.4 3070.29  1182.6 3113.63  1241.6 3151.07
#Mann= 5 ,-1 , 0
       0     .12       0   802.6     .04       0   861.6     .12       0
  910.73    .016       0  940.67     .12       0
#XS Ineff= 2 , 0
          783.97 2968.85
Permanent Ineff=
       F       F
Bank Sta=802.6,861.6
XS Rating Curve= 0 ,0
Exp/Cntr=0.3,0.1

Type RM Length L Ch R = 1 ,52356   ,194.2,173.5,169.8
XS GIS Cut Line= 3
2133703.53174925443282.6851582462133286.16695036443247.639259103
 2132719.0605824443566.238342226
#Sta/Elev= 30
       0 3116.41    48.8 3094.12   129.3 3045.42     149 3041.87   185.2 3028.43
   234.6 3018.25   287.3 3001.59   392.1 2979.06   412.4 2971.45   445.1 2948.72
   565.6 2946.31   598.8 2945.56   642.62948.056   679.2 2959.76   702.9 2972.33
   727.6  2972.4   746.4 2971.72     768 2992.04   776.5 2999.15   794.5 3007.19
   814.1 3025.92   866.8 3060.59   906.9 3094.17     912 3102.14   915.7  3111.1
   930.8 3158.74   934.6 3167.54   999.3 3183.37  1024.9 3196.45  1069.3 3227.33
#Mann= 5 ,-1 , 0
       0     .12       0   565.6     .04       0   642.6     .12       0
   727.6    .016       0     768     .12       0
Bank Sta=565.6,642.6
XS Rating Curve= 0 ,0
Exp/Cntr(USF)=0,0
Exp/Cntr=0.3,0.1

Type RM Length L Ch R = 1 ,52182   ,323.9,328.1,314.3
XS GIS Cut Line= 3
2133442.28050109442712.3927994552133095.00750048443139.315570841
2132684.01468325443496.146543939
#Sta/Elev= 30
       0 3081.21    97.3  3047.7   228.4 3007.86   419.2 2973.82   431.4 2966.23
   445.2 2962.09     461 2951.85   472.6  2947.1   495.9 2945.08   547.2 2945.46
   571.1 2942.04   627.6 2942.86   649.3 2945.88   701.4 2952.62   749.9  2976.1
   777.5 2976.73   798.4 2975.14   810.1 2980.88   831.8 2994.31     855 3000.66
   882.1 3020.89     897 3038.93   920.1 3052.63   975.2  3092.2    1003 3118.29
    1024 3135.13  1040.3 3164.14  1050.2 3173.65  1083.8 3192.37  1094.6 3200.64
#Mann= 5 ,-1 , 0
       0     .12       0   547.2     .04       0   649.3     .12       0
   777.5    .016       0   810.1     .12       0
Bank Sta=547.2,649.3
XS Rating Curve= 0 ,0
Exp/Cntr(USF)=0,0
Exp/Cntr=0.3,0.1

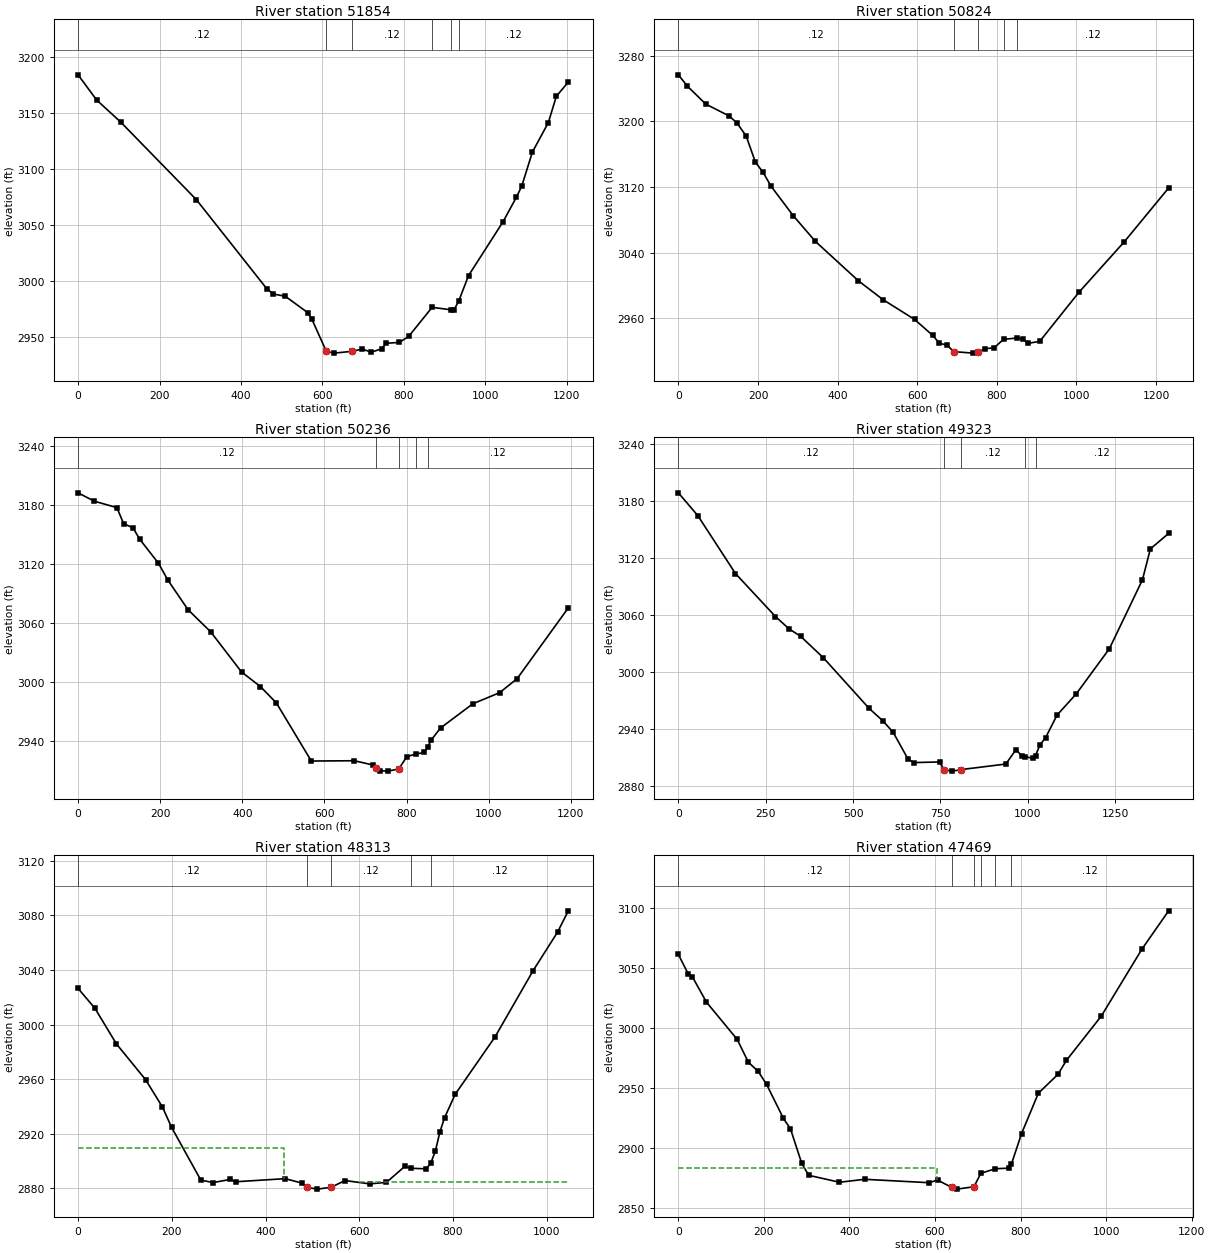
Type RM Length L Ch R = 1 ,51854   ,1041.9,1029.8,995.4
XS GIS Cut Line= 4
     2133013.307       442331.14     2132941.762      442834.815
     2132795.811      443046.587     2132606.933      443441.513
#Sta/Elev= 30
       0 3183.83    45.7 3161.34   104.4 3141.77   290.2 3072.54   463.1 2993.04
   479.4  2988.2   508.7 2986.23   564.1 2971.54   573.8 2965.96   609.6 2937.02
   629.2 2935.45   671.5 2937.03   697.6 2939.02   720.4 2936.31   746.4 2939.47
   756.2 2944.25   788.8    2945   811.7 2950.32  869.34 2976.33  914.78 2974.15
   922.7 2973.85  934.82 2982.03   958.7 3004.62  1043.6 3052.78  1076.3 3074.62
  1089.4  3084.5  1115.5 3114.86  1154.7 3141.19  1174.3 3164.65  1203.7 3177.37
#Mann= 6 ,-1 , 0
       0     .12       0   609.6     .04       0   671.5     .12       0
  869.34    .016       0  914.78     .06       0  934.82     .12       0
Bank Sta=609.6,671.5
XS Rating Curve= 0 ,0
Exp/Cntr=0.3,0.1

Type RM Length L Ch R = 1 ,50824   ,579.6,588.3,589.8
XS GIS Cut Line= 4
     2131860.007       442362.62     2131940.137      442920.668
     2132003.097      443255.497     2132091.812      443570.294
#Sta/Elev= 30
       0 3256.49    22.9 3242.54    68.8 3220.84   127.8 3206.34   147.5  3197.7
   170.4 3181.83   193.4 3150.22     213 3137.58   232.7 3120.93   288.4 3085.05
   344.2 3053.67   452.3 3005.65   514.6 2982.56   593.3 2958.68   639.1 2939.13
   655.5 2929.79   675.2 2927.24   691.5 2919.45   740.7 2917.64   753.8 2919.13
   770.2 2922.96   793.1 2924.18  816.88 2934.42  850.82 2936.05   865.2 2934.75
   878.3 2929.58   907.7 2931.96  1005.9 2991.58  1120.3 3053.32  1231.5 3118.73
#Mann= 5 ,-1 , 0
       0     .12       0   691.5     .04       0   753.8     .12       0
  816.88    .016       0  850.82     .12       0
Bank Sta=691.5,753.8
XS Rating Curve= 0 ,0
Exp/Cntr=0.3,0.1

Type RM Length L Ch R = 1 ,50236   ,903,913.1,907.5
XS GIS Cut Line= 3
     2131590.999      442499.986     2131402.122      443000.798
     2131425.016      443659.009
#Sta/Elev= 30
       0 3192.64    39.2 3184.16    94.6 3177.54     111 3161.17   133.8    3157
   150.1 3145.36   195.8 3120.81   218.7 3103.67   267.6 3073.58   323.1 3050.83
   398.2 3009.94   443.9 2995.15     483 2978.37     568 2919.16   672.9 2919.45
   718.7 2915.04   725.3 2912.33   735.1 2909.25   754.8 2908.86     781 2911.09
   800.7 2923.63  822.19 2926.24   843.2 2927.92  851.74 2933.41   859.6 2940.41
   882.6 2952.81   961.2  2977.5  1026.7 2988.89  1069.3 3003.19  1193.8 3075.34
#Mann= 5 ,-1 , 0
       0     .12       0   725.3     .04       0     781     .12       0
  822.19    .016       0  851.74     .12       0
Bank Sta=725.3,781
XS Rating Curve= 0 ,0
Exp/Cntr=0.3,0.1

Type RM Length L Ch R = 1 ,49323   ,1013.6,1009.9,985.1
XS GIS Cut Line= 4
     2130569.342      442236.702      2130549.31      442883.465
     2130537.862      443238.326     2130586.513      443636.115
#Sta/Elev= 30
       0 3188.63    55.6 3164.64   163.4 3103.67   277.8 3058.47     317 3045.37
   349.7 3037.71     415 3015.02   545.8 2961.79     585 2948.73   614.4 2936.73
   656.8 2908.69   673.1 2904.76     748 2905.42  759.42 2897.38   783.9 2895.77
   809.9 2897.43     937 2903.24   966.3 2918.44   982.6 2911.73  992.28 2910.84
  1015.2 2909.34 1021.97 2912.19  1034.7 2923.36    1051 2931.13  1083.6 2954.73
    1139 2977.27  1233.4 3024.62  1327.9 3097.02  1350.7 3129.66  1402.9 3145.89
#Mann= 5 ,-1 , 0
       0     .12       0  759.42     .04       0   809.9     .12       0
  992.28    .016       0 1021.97     .12       0
Bank Sta=759.42,809.9
XS Rating Curve= 0 ,0
Exp/Cntr=0.3,0.1

Type RM Length L Ch R = 1 ,48313   ,852.1,843.8,831.3
XS GIS Cut Line= 3
     2129473.278      443106.684     2129825.278      443704.798
     2130074.253      443953.773
#Sta/Elev= 30
       0 3026.44      36 3011.88    81.8 2985.83     144 2959.68     180 2939.67
   199.7 2924.65   261.9 2886.13   288.1  2884.3   324.1 2886.57   337.2 2884.92
   441.9 2887.17     478 2883.92   487.8 2880.85   510.7 2879.51   540.2 2880.88
   569.6 2885.81     622 2883.37     658 2884.46   697.3 2896.14  710.64 2894.76
   742.9 2894.38  752.41 2898.36   762.5 2907.45   772.2 2921.53     782 2931.72
   804.8 2948.96   889.6 2990.85   971.1 3039.47  1023.3  3067.7  1046.1 3083.22
#Mann= 5 ,-1 , 0
       0     .12       0   487.8     .04       0   540.2     .12       0
  710.64    .016       0  752.41     .12       0
#XS Ineff= 2 , 0
          440.48 2909.42  599.91         2884.91
Permanent Ineff=
       F       F
Bank Sta=487.8,540.2
XS Rating Curve= 0 ,0
Exp/Cntr=0.3,0.1

Type RM Length L Ch R = 1 ,47469   ,482.1,483.7,479.3
XS GIS Cut Line= 2
     2128809.344      443827.854     2129713.668      444531.854
#Sta/Elev= 30
       0 3060.95    22.9 3044.86    32.7 3042.39    65.5 3021.31   137.5  2990.2
   163.7  2971.1   186.6 2963.57   206.3 2952.67   245.6 2924.34     262 2915.74
   288.2  2887.1   304.5 2877.01   376.6  2871.2   435.5 2873.66   586.1 2870.82
   605.8 2873.06   638.5 2866.98   651.6 2865.47   690.9 2867.47  707.19 2878.67
  740.93 2882.46   772.8 2882.93  778.36 2886.17   802.2 2911.73   841.5 2945.38
   887.4 2961.12     907  2972.7   988.9 3009.79  1083.8 3065.55    1146 3097.33
#Mann= 6 ,-1 , 0
       0     .12       0   638.5     .04       0   690.9     .12       0
  707.19     .08       0  740.93    .016       0  778.36     .12       0
#XS Ineff= 2 , 0
          603.73 2882.71
Permanent Ineff=
       F       F
Bank Sta=638.5,690.9
XS Rating Curve= 0 ,0
Exp/Cntr=0.3,0.1

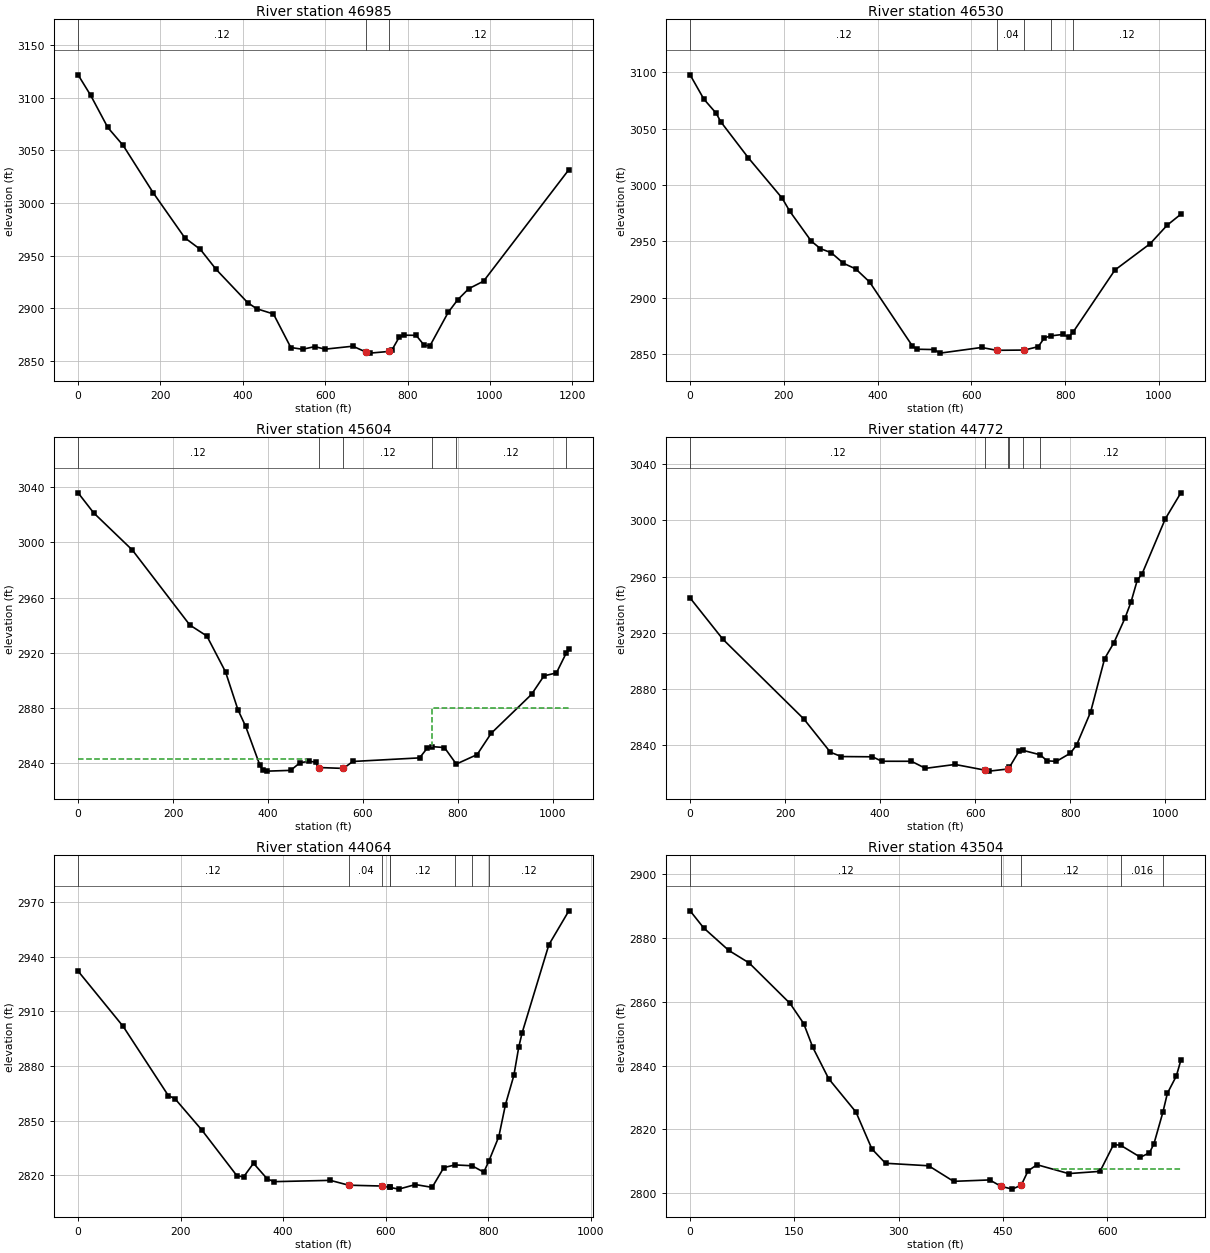
Type RM Length L Ch R = 1 ,46985   ,446.7,455.7,444.2
XS GIS Cut Line= 2
2128481.66428449444170.3973212252129423.02944179444900.694057605
#Sta/Elev= 30
       0 3121.77    30.6 3102.26    72.1 3071.76   109.5 3054.67   182.3 3009.77
     259    2967   296.9 2955.93   335.1 2936.98   411.5 2905.46   433.4 2899.63
   474.3 2894.63   516.4 2862.78   544.8  2861.1   574.6 2863.61   599.5  2861.2
     667 2864.01   698.52858.537   708.5 2857.44   754.12859.026   762.2 2860.65
   779.4 2872.45   790.3 2874.49   820.7 2874.34   840.3 2864.84   854.3 2864.44
   898.4  2896.1   921.2 2907.96   948.3 2918.62   984.4  2925.8  1191.4 3031.69
#Mann= 3 , 0 , 0
       0     .12       0   698.5     .04       0   754.1     .12       0
Bank Sta=698.5,754.1
XS Rating Curve= 0 ,0
Exp/Cntr(USF)=0,0
Exp/Cntr=0.3,0.1

Type RM Length L Ch R = 1 ,46530   ,912.3,925.4,924.7
XS GIS Cut Line= 2
     2128231.263      444531.854     2129061.181      445170.032
#Sta/Elev= 30
       0 3097.67    29.4 3076.11    55.6 3063.63    65.4 3056.09   124.3 3024.06
   196.3 2988.39   212.6 2976.77   258.5 2950.24   278.1 2943.58     301 2940.02
   327.2 2930.62   353.3 2925.64   382.8 2914.09   474.4  2857.2   484.2 2854.46
   520.2 2854.16   533.3    2851   621.6 2856.01   654.3  2853.5   713.2 2853.72
   742.7 2856.74   755.7 2864.47   769.1 2866.28     795 2867.56   808.1 2865.32
  817.55 2869.99   906.2 2924.66   981.5 2948.04  1017.5 2964.34  1046.9 2974.14
#Mann= 5 ,-1 , 0
       0     .12       0   654.3     .04       0   713.2     .12       0
   769.1    .016       0  817.55     .12       0
Bank Sta=654.3,713.2
XS Rating Curve= 0 ,0
Exp/Cntr=0.3,0.1

Type RM Length L Ch R = 1 ,45604   ,826.6,832.4,829.9
XS GIS Cut Line= 3
     2127676.077      444995.463     2128091.036      445479.105
     2128319.979      445802.486
#Sta/Elev= 30
       0  3036.1    32.7 3021.58   114.4 2994.46   235.3    2940   271.2    2932
   310.5 2905.95   336.6 2878.44   352.9 2866.32   382.4  2838.5   388.9 2834.41
   398.7 2833.79   447.7 2834.34   467.3 2839.91   486.9 2840.92     500 2840.31
   506.5 2836.42   558.8 2835.76   578.4  2840.8   719.1 2843.42   735.5 2850.59
  745.33 2851.61   771.5 2850.92  796.45 2838.92   840.3 2845.81   869.8 2861.24
   954.9 2889.58   981.1 2903.05  1007.3 2905.18 1028.18 2919.77  1033.5 2922.59
#Mann= 6 ,-1 , 0
       0     .12       0   506.5     .04       0   558.8     .12       0
  745.33    .016       0  796.45     .12       0 1028.18    .016       0
#XS Ineff= 2 , 0
             480 2842.38  744.43         2879.83
Permanent Ineff=
       F       F
Bank Sta=506.5,558.8
XS Rating Curve= 0 ,0
Exp/Cntr=0.3,0.1

Type RM Length L Ch R = 1 ,44772   ,716.5,707.8,670
XS GIS Cut Line= 3
     2127109.443      445467.657     2127561.605      446091.527
     2127707.557      446309.022
#Sta/Elev= 30
       0 2944.84    68.8 2915.56   239.4 2858.75   295.1 2835.17     318 2832.08
   383.6 2831.91   403.3 2828.74   465.6 2828.72   495.1  2823.7   557.4 2826.46
   619.7 2822.46   629.5 2821.72   668.9 2823.25   671.8  2824.5   691.8 2835.82
  700.01 2836.52  736.49 2833.33   750.8 2829.03   770.5 2828.66     800 2834.47
   813.1 2840.34   842.5 2863.73     872  2901.7   891.6 2913.09   914.6 2930.32
   927.6 2942.06   940.8 2957.63   950.6 2961.84   999.7 3001.14  1032.4 3019.61
#Mann= 6 ,-1 , 0
       0     .12       0   619.7     .04       0   668.9     .12       0
   671.8     .08       0  700.01    .016       0  736.49     .12       0
Bank Sta=619.7,668.9
XS Rating Curve= 0 ,0
Exp/Cntr=0.3,0.1

Type RM Length L Ch R = 1 ,44064   ,562.9,559.7,542.5
XS GIS Cut Line= 4
     2126436.924      446317.608     2126786.062      446383.429
     2127100.858      446466.421     2127346.972      446592.339
#Sta/Elev= 30
       0 2932.14      88 2901.72     176 2863.72     189    2862   241.2 2844.86
   309.6 2819.73   322.7 2818.99   342.2 2826.51   368.3 2818.14   381.3 2816.41
     492 2817.13   527.8 2814.47   592.9 2814.01  608.45 2813.25  608.71 2813.24
   625.5 2812.31     658 2814.82   690.6 2813.28   713.4 2824.13   735.2 2825.62
  768.38 2825.15   791.4 2821.64  801.56 2827.93   820.7 2841.18   833.7 2858.82
     850 2874.78   859.7 2890.58   866.2 2898.27   918.3 2946.62   957.3 2965.27
#Mann= 8 ,-1 , 0
       0     .12       0   527.8     .04       0   592.9     .12       0
  608.45     .08       0  608.71     .12       0   735.2     .08       0
  768.38    .016       0  801.56     .12       0
#XS Ineff= 2 , 0
          497.55 2816.71
Permanent Ineff=
       F       F
Bank Sta=527.8,592.9
XS Rating Curve= 0 ,0
Exp/Cntr=0.3,0.1

Type RM Length L Ch R = 1 ,43504   ,412.4,405.6,392.1
XS GIS Cut Line= 4
     2126594.322      446984.404     2126952.045        446947.2
     2127129.476      446967.233     2127292.598      446927.168
#Sta/Elev= 30
       0 2888.53    19.6 2883.16    55.6 2876.13      85 2872.18   143.9 2859.48
   163.5 2853.17   176.6 2845.71   199.4  2835.9   238.7 2825.44   261.6 2813.88
   281.2  2809.4   343.3 2808.61   379.1 2803.73   431.1 2804.17   447.3 2802.18
   463.5 2801.29   476.5 2802.53   486.3 2807.01   499.2 2808.94   544.7 2806.16
   589.9 2806.86   609.3 2815.24  619.41 2815.06     648 2811.28     661 2812.68
   667.4 2815.48  680.23 2825.32   686.8 2831.34   699.7 2836.76   706.2 2841.72
#Mann= 5 ,-1 , 0
       0     .12       0   447.3     .04       0   476.5     .12       0
  619.41    .016       0  680.23     .12       0
#XS Ineff= 2 , 0
                          522.36         2807.56
Permanent Ineff=
       F       F
Bank Sta=447.3,476.5
XS Rating Curve= 0 ,0
Exp/Cntr=0.3,0.1

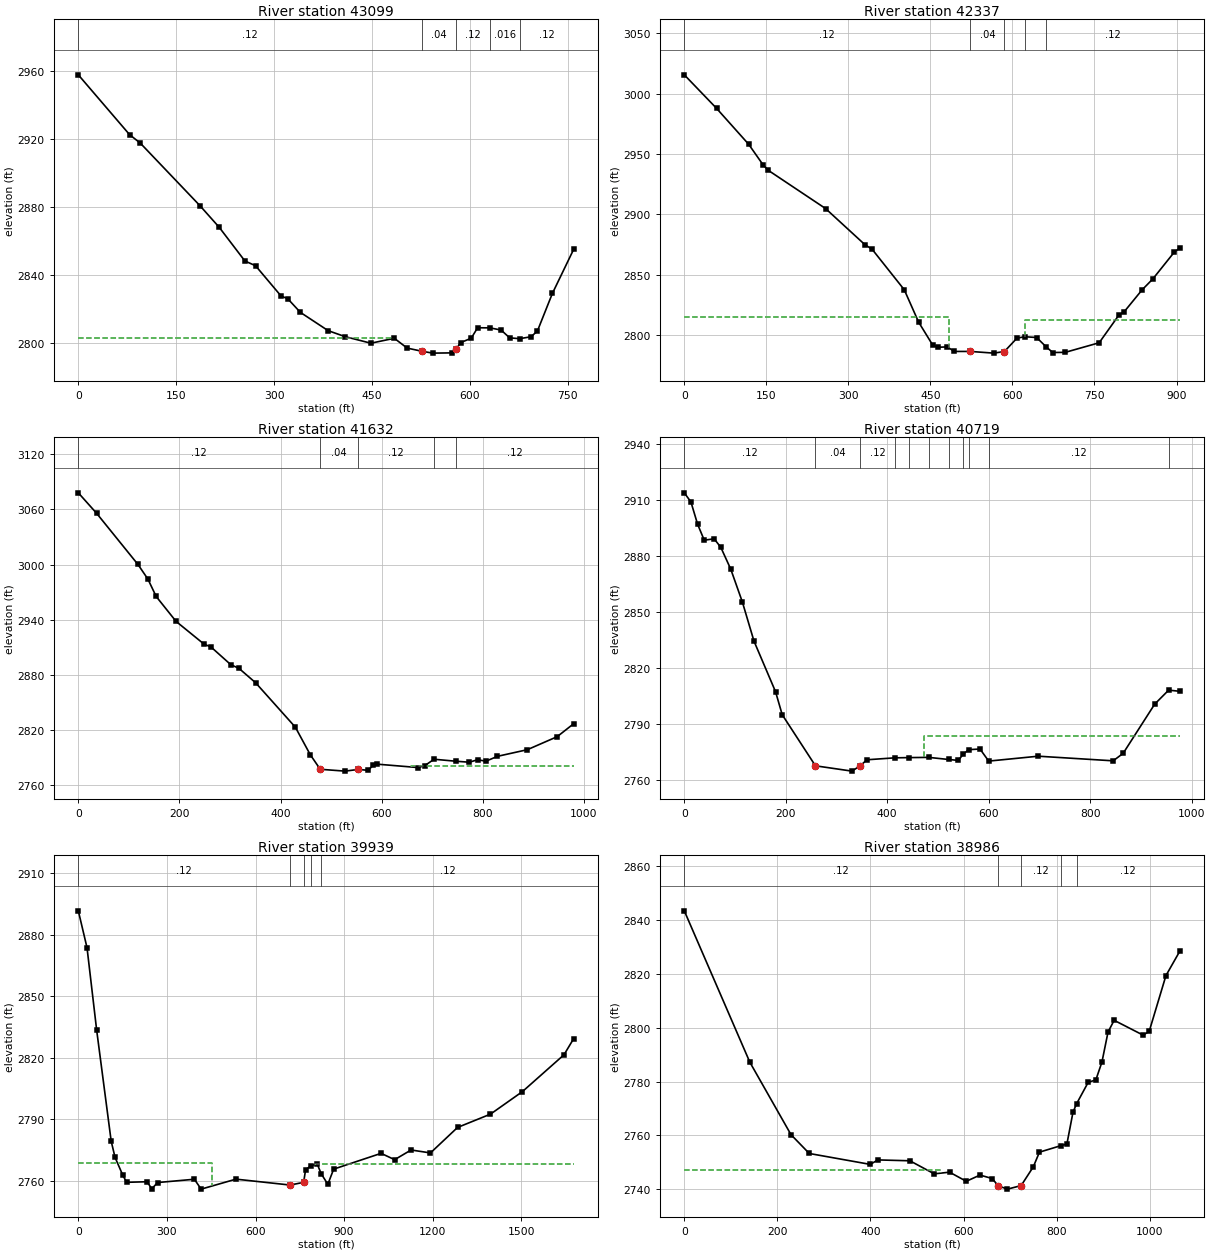
Type RM Length L Ch R = 1 ,43099   ,752.3,761.4,749.8
XS GIS Cut Line= 2
     2126860.468      447553.899     2127449.996      447075.981
#Sta/Elev= 30
       0 2957.98    78.5 2922.79    94.9  2917.8   186.5 2880.89   215.9 2868.21
   255.2  2848.4   271.5 2845.62   310.8  2827.7   320.6 2826.29   340.2 2818.16
   382.7  2807.4   408.9 2803.85   448.2 2800.01   484.1  2802.9   503.8 2797.13
   526.7 2795.25     543 2794.17   572.5 2794.32     579 2796.52   585.5 2800.32
   601.9 2802.95   611.7  2809.1  630.52 2809.05   647.7 2807.75   660.8 2803.17
  675.95 2802.67   693.5  2803.8   703.3 2807.17   726.2 2829.27   758.9 2855.32
#Mann= 5 ,-1 , 0
       0     .12       0   526.7     .04       0     579     .12       0
  630.52    .016       0  675.95     .12       0
#XS Ineff= 2 , 0
          482.53 2803.07
Permanent Ineff=
       F       F
Bank Sta=526.7,579
XS Rating Curve= 0 ,0
Exp/Cntr=0.3,0.1

Type RM Length L Ch R = 1 ,42337   ,701.3,705.4,694
XS GIS Cut Line= 2
     2127352.695      448129.118     2128045.247      447545.314
#Sta/Elev= 30
       0  3015.7    58.9 2987.93   117.7 2958.08   143.9 2941.12   153.7 2936.42
   258.3 2904.76   330.3 2874.76   343.4    2871   402.2 2837.39   428.4 2810.58
   454.5 2791.27   464.3  2789.7   480.7 2789.97   493.8 2786.21   523.2 2786.21
   565.7 2784.81   585.3 2786.12   608.2 2797.22  622.43 2798.42   644.2 2797.77
  661.06 2790.29   673.6 2785.33   696.5 2785.45   758.6 2793.42   794.6 2816.34
   804.4 2819.17   837.1 2837.32   856.7 2846.36     896 2868.65   905.8 2871.96
#Mann= 5 ,-1 , 0
       0     .12       0   523.2     .04       0   585.3     .12       0
  622.43    .016       0  661.06     .12       0
#XS Ineff= 2 , 0
           483.7 2815.19  623.52          2812.3
Permanent Ineff=
       F       F
Bank Sta=523.2,585.3
XS Rating Curve= 0 ,0
Exp/Cntr=0.3,0.1

Type RM Length L Ch R = 1 ,41632   ,912.8,912.7,896.8
XS GIS Cut Line= 2
     2127764.792      448707.199     2128471.653      448028.955
#Sta/Elev= 30
       0 3078.06      36  3055.9     118 3000.04   137.6 2984.15     154 2965.21
   193.3 2938.11     249 2913.18   262.1 2910.39   301.4 2891.05   317.8 2886.92
   350.6 2871.32   429.2 2822.93   458.7 2792.96   478.4 2777.12   527.5 2775.11
   553.7 2776.96   573.4 2775.96   583.2 2781.73   589.7 2782.75   671.6 2779.02
   684.8 2780.96  703.49 2788.05  746.16 2785.91   773.2 2784.81   789.6 2787.51
     806 2785.92   828.9 2791.23   887.9 2798.44   946.9  2812.6   979.6 2826.74
#Mann= 5 ,-1 , 0
       0     .12       0   478.4     .04       0   553.7     .12       0
  703.49    .016       0  746.16     .12       0
#XS Ineff= 2 , 0
                          658.55         2780.45
Permanent Ineff=
       F       F
Bank Sta=478.4,553.7
XS Rating Curve= 0 ,0
Exp/Cntr=0.3,0.1

Type RM Length L Ch R = 1 ,40719   ,738.4,780.1,797.4
XS GIS Cut Line= 4
      2128563.23      449205.149     2128700.596      449064.922
       2128835.1      448887.491      2129204.27       448469.67
#Sta/Elev= 30
       0 2913.66    13.1 2908.76    26.2 2896.86    39.3 2888.31    58.9 2889.04
      72 2884.46    91.6 2872.78   114.5 2855.19   137.4 2834.25   179.9 2807.17
     193 2794.88   258.5 2767.52   330.5 2764.67   346.9 2767.57     360 2770.75
   415.2 2771.79  442.38 2771.91  481.79 2772.03  521.21  2770.9   540.3  2770.4
  549.35 2773.64  560.62 2776.16   582.9 2776.51  600.04 2770.04   697.7 2772.66
   845.3 2770.19     865 2774.16   927.3 2800.55  954.76 2808.03   976.5 2807.41
#Mann= 11 ,-1 , 0
       0     .12       0   258.5     .04       0   346.9     .12       0
   415.2     .06       0  442.38     .12       0  481.79    .016       0
  521.21     .06       0  549.35     .08       0  560.62    .016       0
  600.04     .12       0  954.76    .016       0
#XS Ineff= 2 , 0
                          473.15         2783.63
Permanent Ineff=
       F       F
Bank Sta=258.5,346.9
XS Rating Curve= 0 ,0
Exp/Cntr=0.3,0.1

Type RM Length L Ch R = 1 ,39939   ,921.4,953.2,960.7
XS GIS Cut Line= 3
     2128577.539      449291.003      2129347.36      449517.084
     2130100.009      449963.522
#Sta/Elev= 30
       0 2891.65    29.5 2873.68    62.2 2833.46   111.3 2779.44   124.4 2771.54
   150.6 2762.87   163.7  2759.4   232.5 2759.68   248.9 2756.26   268.5 2759.29
     393 2760.89   415.9 2756.08   533.8 2760.94   717.2 2758.07     763 2759.39
   769.6 2765.59  789.41 2767.57   808.9 2768.33  822.25 2763.62   844.9 2758.43
   864.6 2765.82  1025.2 2773.51  1071.1 2770.43  1126.8 2775.15  1192.4 2773.71
  1284.1 2786.13  1395.6 2792.61  1503.7 2803.58  1644.6 2821.54  1677.4 2829.41
#Mann= 5 ,-1 , 0
       0     .12       0   717.2     .04       0     763     .08       0
  789.41    .016       0  822.25     .12       0
#XS Ineff= 2 , 0
           452.6 2769.05  801.81         2768.34
Permanent Ineff=
       F       F
Bank Sta=717.2,763
XS Rating Curve= 0 ,0
Exp/Cntr=0.3,0.1

Type RM Length L Ch R = 1 ,38986   ,358.3,357.4,356
XS GIS Cut Line= 2
     2128357.182      449528.531     2128889.474      450450.026
#Sta/Elev= 30
       0 2843.43   140.8  2787.2   229.2 2760.29   268.5 2753.29   399.5 2749.24
   415.8  2750.9   484.6 2750.58     537 2745.72   569.8 2746.35   605.8 2742.96
   635.2 2745.27   661.4 2743.99   674.5 2741.26   694.2 2740.05   723.6 2741.36
   749.8 2748.35   762.9 2753.78  808.47 2756.17   821.9 2756.79     835 2768.62
  842.58 2771.72   867.7 2779.74   884.1 2780.61   897.2 2787.27   910.3 2798.42
   923.4 2802.76   985.6 2797.26   998.7 2798.65  1034.7 2819.38  1064.2 2828.36
#Mann= 5 ,-1 , 0
       0     .12       0   674.5     .04       0   723.6     .12       0
  808.47    .016       0  842.58     .12       0
#XS Ineff= 2 , 0
           551.5 2747.09
Permanent Ineff=
       F       F
Bank Sta=674.5,723.6
XS Rating Curve= 0 ,0
Exp/Cntr=0.3,0.1

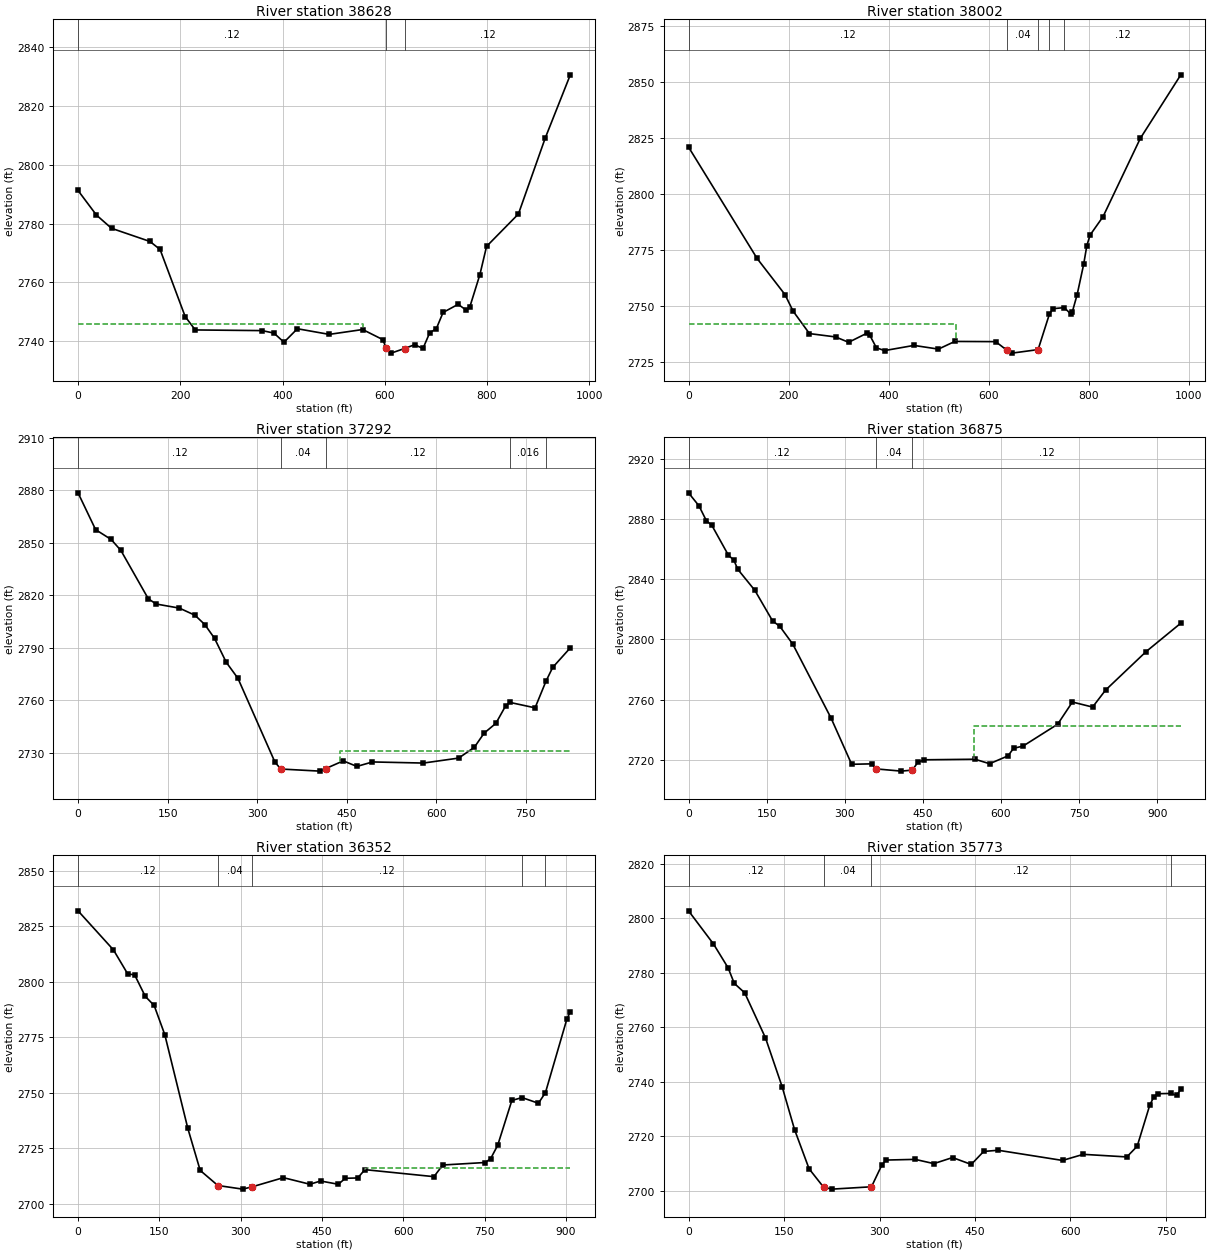
Type RM Length L Ch R = 1 ,38628   ,614.1,626,640.4
XS GIS Cut Line= 2
     2128072.994      449818.544     2128607.175      450619.816
#Sta/Elev= 30
       0 2791.24      36 2782.89    65.5 2778.39   140.8 2773.91   160.5 2771.19
   209.6  2748.4   229.3 2743.85   360.3 2743.62   383.2 2742.78   402.9 2739.67
   429.1 2744.26   491.3 2742.34   556.8 2743.99   596.2 2740.56   602.7 2737.67
   612.5 2735.97   638.7 2737.54   658.4 2738.83   674.8 2737.56   687.9 2742.85
     701 2744.32   714.1 2749.79   743.6 2752.56   759.9  2750.5   766.5 2751.71
   786.1 2762.64   799.2 2772.25   861.5 2783.26   913.9 2809.04     963 2830.55
#Mann= 3 , 0 , 0
       0     .12       0   602.7     .04       0   638.7     .12       0
#XS Ineff= 2 , 0
           557.8 2745.85
Permanent Ineff=
       F       F
Bank Sta=602.7,638.7
XS Rating Curve= 0 ,0
Exp/Cntr=0.3,0.1

Type RM Length L Ch R = 1 ,38002   ,717.4,710.9,681.2
XS GIS Cut Line= 3
     2127847.784       449831.88     2127844.922      450570.221
      2127842.06      450816.334
#Sta/Elev= 30
       0  2820.9   137.2 2771.23   192.8 2755.18   209.1 2747.78   241.8 2737.76
     294 2736.27   320.2 2733.88   356.1 2737.86   362.6    2737   375.7 2731.43
     392 2730.18   450.8 2732.49   499.8 2730.84   532.5 2734.26   614.2 2734.17
   637.1 2730.28   646.9 2729.05   699.1 2730.62  721.63 2746.38   728.6 2748.84
  751.17 2749.34   764.2  2746.6   767.5 2747.41   777.2 2755.13   790.2  2768.6
   796.6 2776.99   803.1 2781.69     829 2789.89   903.5 2824.76   984.5  2853.1
#Mann= 5 ,-1 , 0
       0     .12       0   637.1     .04       0   699.1     .12       0
  721.63    .016       0  751.17     .12       0
#XS Ineff= 2 , 0
          534.68  2742.2
Permanent Ineff=
       F       F
Bank Sta=637.1,699.1
XS Rating Curve= 0 ,0
Exp/Cntr=0.3,0.1

Type RM Length L Ch R = 1 ,37292   ,414.3,416.8,407.3
XS GIS Cut Line= 3
     2127143.785      449886.254     2127284.012      450355.587
     2127358.419      450681.831
#Sta/Elev= 30
       0  2878.5    29.4 2857.48    55.5 2851.83    71.8 2845.56   117.6    2818
   130.6 2814.97   169.8 2812.61   195.9 2808.53   212.3 2803.21   228.6 2795.35
   248.2 2781.66   267.8 2772.48   329.8 2724.56   339.6 2720.65   404.9 2719.45
   414.7 2720.89   444.1 2725.31     467 2722.14   493.1  2724.7   578.4 2724.06
   637.5 2726.91   663.7 2733.07   680.1 2741.17   699.8 2746.77   716.2 2756.82
  723.13 2758.73   765.4 2755.62  783.72 2770.88   794.9 2778.72   824.4 2789.91
#Mann= 5 ,-1 , 0
       0     .12       0   339.6     .04       0   414.7     .12       0
  723.13    .016       0  783.72     .12       0
#XS Ineff= 2 , 0
                          439.31         2731.22
Permanent Ineff=
       F       F
Bank Sta=339.6,414.7
XS Rating Curve= 0 ,0
Exp/Cntr=0.3,0.1

Type RM Length L Ch R = 1 ,36875   ,531.7,522.4,516.7
XS GIS Cut Line= 2
 2126738.2391277450059.2062648622127088.61270642450937.250895885
#Sta/Elev= 30
       0 2897.23    20.1 2888.57    34.2 2878.76    44.8 2875.65    76.6 2855.84
      87 2852.59    94.6 2846.48   127.4 2832.51   161.4 2812.26   175.4  2808.6
   200.3  2796.8   273.8 2747.72   313.3 2717.12   352.1 2717.41   359.7 2714.08
   408.7 2712.58   429.9 2713.27   440.4 2718.45   453.1  2720.1     550 2720.47
   578.2  2717.5   613.6 2722.71   624.2 2727.72   642.5  2729.2   708.9  2743.7
   737.2 2758.43     776 2755.08   800.8  2766.3   878.5  2791.8   945.4 2810.74
#Mann= 3 , 0 , 0
       0     .12       0   359.7     .04       0   429.9     .12       0
#XS Ineff= 2 , 0
                          548.89         2742.74
Permanent Ineff=
       F       F
Bank Sta=359.7,429.9
XS Rating Curve= 0 ,0
Exp/Cntr(USF)=0,0
Exp/Cntr=0.3,0.1

Type RM Length L Ch R = 1 ,36352   ,592.6,579.2,566.5
XS GIS Cut Line= 3
     2126233.737       450392.79     2126491.298      450721.896
     2126826.127      451079.619
#Sta/Elev= 30
       0  2831.9    65.3 2814.33    91.4  2803.6   104.5 2803.03   124.1 2793.38
   140.4 2789.32     160  2776.2   202.4  2734.1   225.3 2715.11   257.9 2708.32
   303.6 2706.69     320 2707.65   378.7 2711.85   427.7 2708.88   447.3 2710.35
     480 2708.88     493 2711.56   515.9 2711.72     529 2715.46   656.4  2712.3
   672.7 2717.54   751.1 2718.67   760.9 2720.37     774 2726.42   800.1 2746.59
  818.89 2747.88   849.1 2745.32  862.11 2750.14   901.4 2783.05   907.9 2786.54
#Mann= 5 ,-1 , 0
       0     .12       0   257.9     .04       0     320     .12       0
  818.89    .016       0  862.11     .12       0
#XS Ineff= 2 , 0
                          529.35         2716.06
Permanent Ineff=
       F       F
Bank Sta=257.9,320
XS Rating Curve= 0 ,0
Exp/Cntr=0.3,0.1

Type RM Length L Ch R = 1 ,35773   ,525.1,510.5,497.2
XS GIS Cut Line= 3
     2125921.802      451005.212     2126273.802       451145.44
     2126631.525      451311.423
#Sta/Elev= 30
       0 2802.76    39.2 2790.58    62.1 2781.85    71.9  2776.1    88.2 2772.65
   120.9 2756.07     147 2738.18   166.6 2722.36   189.4 2707.98   212.3 2701.19
   225.4 2700.52   287.4 2701.38   303.8 2709.43   310.3  2711.2     356 2711.45
   385.4 2709.89   414.8 2712.12   444.1 2709.59   463.6 2714.36   486.4  2714.8
   587.5 2711.06   620.1  2713.3   688.5 2712.35   704.8 2716.28   724.4 2731.26
   730.9 2734.44   737.4 2735.57  757.94 2735.67   766.7 2734.96   773.3  2737.2
#Mann= 4 ,-1 , 0
       0     .12       0   212.3     .04       0   287.4     .12       0
  757.94    .016       0
Bank Sta=212.3,287.4
XS Rating Curve= 0 ,0
Exp/Cntr=0.3,0.1