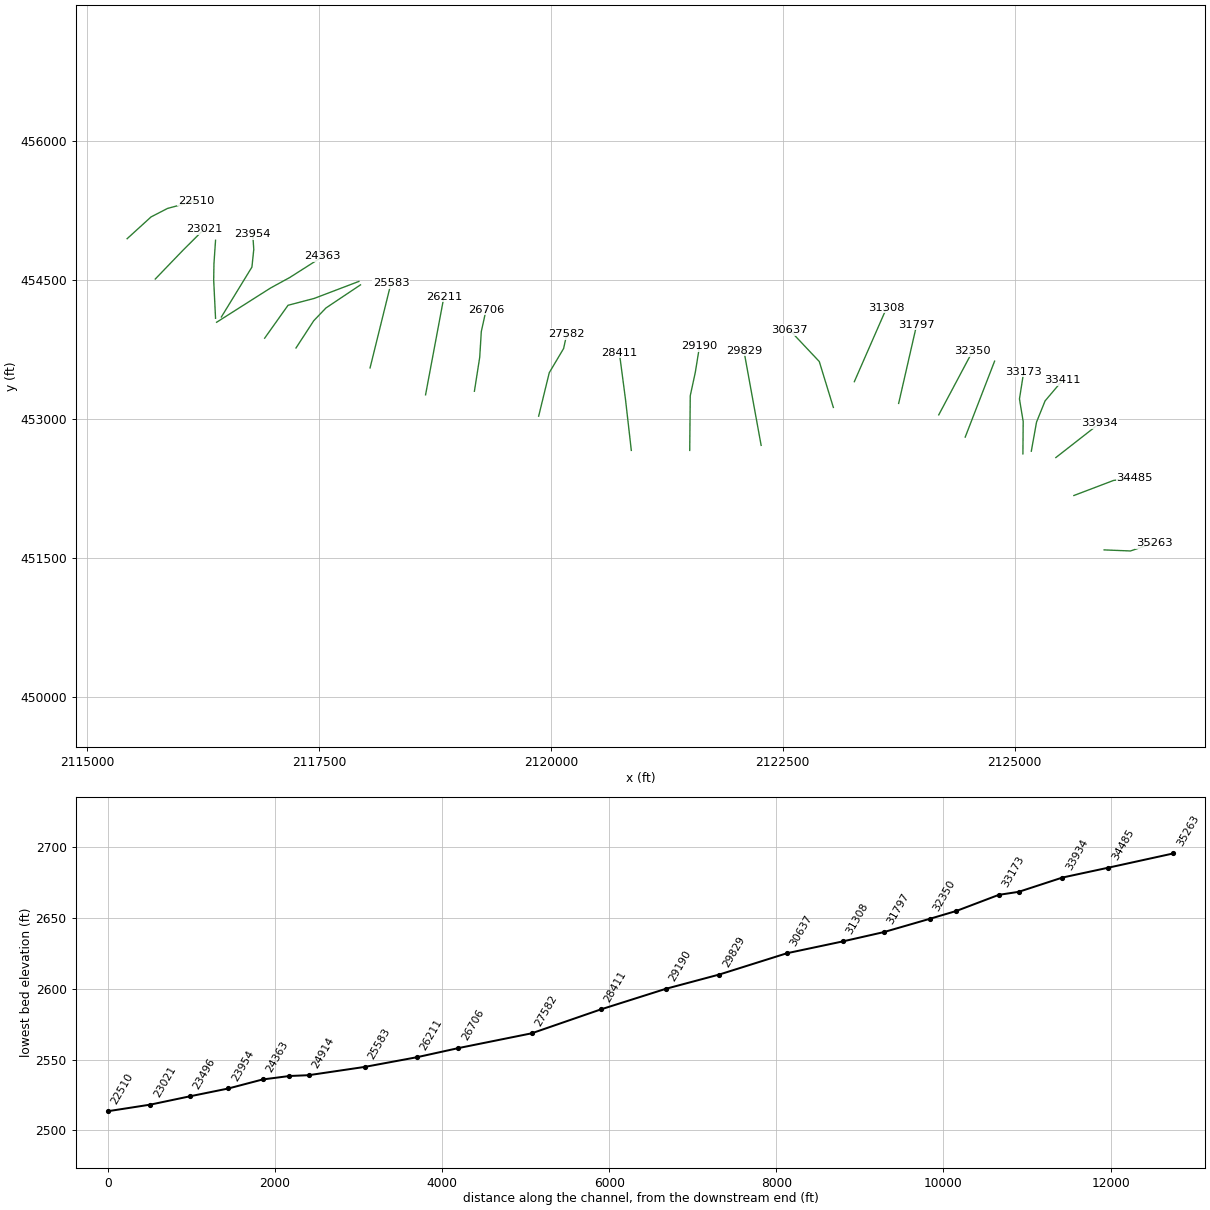
HEC-RAS study NFKCHERRYRV.prj: NFKCHERRYRV

--- NFKCHERRYRV.g01 (geometry) --- (continued)

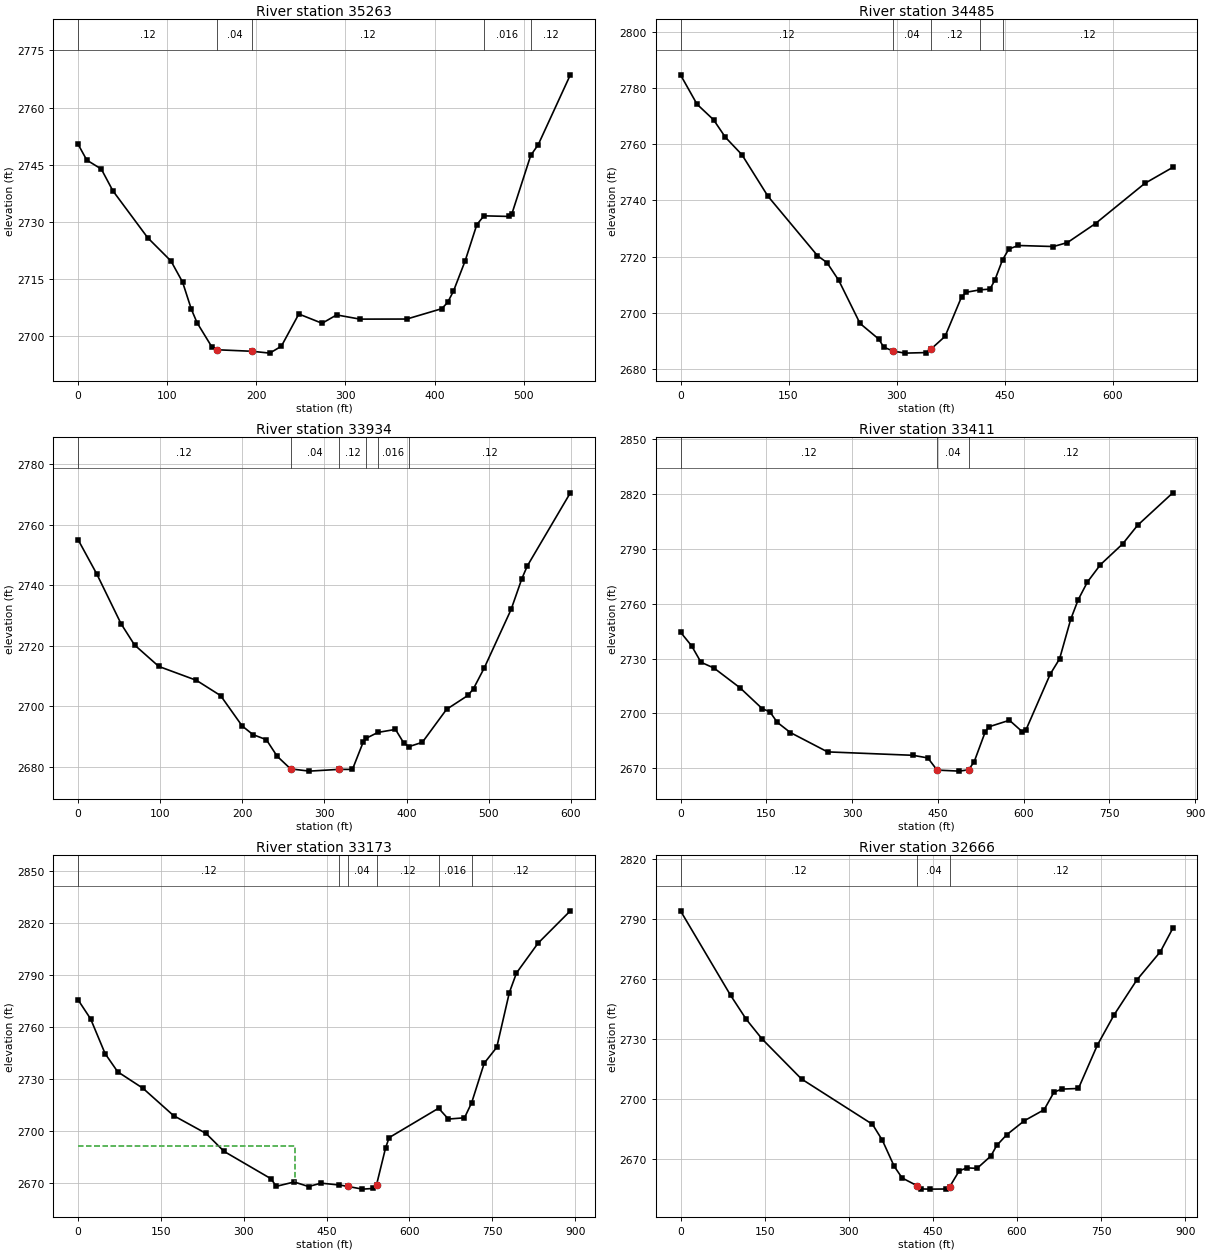
Type RM Length L Ch R = 1 ,35263   ,762.9,777.5,779.2
XS GIS Cut Line= 3
     2125964.729      451586.155     2126248.046      451574.708
     2126502.745      451660.561
#Sta/Elev= 30
       0 2750.42     9.8 2746.25    26.1  2743.9    39.1 2738.19    78.2 2725.87
   104.3 2719.77   117.3 2714.24   127.1 2707.14   133.6 2703.57   149.9 2697.33
   156.4  2696.5   195.6  2696.1   215.1 2695.62   228.1 2697.43   247.7 2705.88
   273.8 2703.45   290.1 2705.64   316.3 2704.54   368.8 2704.56   408.1 2707.28
   414.7 2708.94   421.2 2711.89   434.3 2719.82   447.4 2729.32  455.38 2731.63
   483.5 2731.47   486.8 2732.21  507.86 2747.47   516.3  2750.3   552.3 2768.61
#Mann= 5 ,-1 , 0
       0     .12       0   156.4     .04       0   195.6     .12       0
  455.38    .016       0  507.86     .12       0
Bank Sta=156.4,195.6
XS Rating Curve= 0 ,0
Exp/Cntr=0.3,0.1

Type RM Length L Ch R = 1 ,34485   ,542.2,551.2,558
XS GIS Cut Line= 3
     2125638.486      452172.821     2126067.753      452335.943
     2126290.973      452358.837
#Sta/Elev= 30
       0 2784.77      23 2774.27    45.9 2768.75    62.3 2762.52    85.3 2756.29
   121.4  2741.5   190.2  2720.3   203.4 2717.82   219.8 2711.47   249.3 2696.14
   275.5 2690.52   282.1 2687.71   295.2  2686.3   311.6 2685.56   341.1 2685.76
   347.7 2686.97   367.4 2691.55   390.3 2705.62   396.9 2707.26  415.53 2708.11
   429.7 2708.38   436.3 2711.47  447.12 2718.78   455.9 2722.66     469 2723.93
   517.8 2723.56   537.3 2724.97   576.3 2731.77   644.6 2746.05   683.6 2751.79
#Mann= 5 ,-1 , 0
       0     .12       0   295.2     .04       0   347.7     .12       0
  415.53    .016       0  447.12     .12       0
Bank Sta=295.2,347.7
XS Rating Curve= 0 ,0
Exp/Cntr=0.3,0.1

Type RM Length L Ch R = 1 ,33934   ,505.2,522.7,534.5
XS GIS Cut Line= 2
     2125443.884      452582.056     2125916.079      452951.226
#Sta/Elev= 30
       0 2755.05    22.9 2743.65    52.4 2727.24    68.8 2720.25    98.3 2713.16
   144.1 2708.57   173.6 2703.51   199.8  2693.5   212.9 2690.65   229.3 2688.95
   242.4  2683.5   258.8 2679.31   281.7 2678.57   317.7 2679.15   334.1 2679.13
   347.2 2688.16  351.05 2689.45  365.15 2691.36   386.5 2692.35   396.3 2687.99
  402.64 2686.64   419.2 2688.09   448.7 2698.98   474.9 2703.61   481.5 2705.83
   494.6 2712.66   527.3 2731.98   540.4 2742.17     547 2746.34   599.4  2770.5
#Mann= 6 ,-1 , 0
       0     .12       0   258.8     .04       0   317.7     .12       0
  351.05     .06       0  365.15    .016       0  402.64     .12       0
Bank Sta=258.8,317.7
XS Rating Curve= 0 ,0
Exp/Cntr=0.3,0.1

Type RM Length L Ch R = 1 ,33411   ,220.4,238.3,249.9
XS GIS Cut Line= 4
     2125179.515      452650.816     2125235.798      452964.754
     2125327.995      453193.395     2125518.823      453418.979
#Sta/Elev= 30
       0  2744.4    19.5 2736.88    35.8 2727.95    58.6 2724.78   104.1 2713.99
   143.2 2702.52   156.2 2700.93   169.2 2695.14     192 2689.58   257.1    2679
   406.5 2677.13   432.5  2675.7   448.7 2669.06   487.6 2668.49   503.8 2669.23
   513.6 2673.64     533 2690.02   539.5 2692.71   575.2 2696.27   597.9 2689.93
   604.4 2691.22   646.6 2721.49   662.9  2729.8   682.4 2751.43   695.4 2762.06
   711.6 2771.79   734.3 2781.23   773.3 2792.62   799.2 2802.71   860.9 2820.48
#Mann= 3 , 0 , 0
       0     .12       0   448.7     .04       0   503.8     .12       0
Bank Sta=448.7,503.8
XS Rating Curve= 0 ,0
Exp/Cntr=0.3,0.1

Type RM Length L Ch R = 1 ,33173   ,514.8,507,483.2
XS GIS Cut Line= 4
     2125089.023      452622.121     2125091.885      452971.259
      2125051.82      453214.511     2125097.608      453506.413
#Sta/Elev= 30
       0 2775.69    22.8 2764.65      49 2744.62    71.8 2734.11   117.5  2724.6
   172.9 2708.82   231.7 2698.52   264.3 2688.16   349.2 2672.37   358.9 2667.98
   391.3 2670.49   417.3 2667.86     440 2669.81  473.19 2668.73   488.6 2667.93
   514.6 2666.36     534 2666.73   540.5 2669.02   556.8 2690.25   563.2  2696.1
  652.72 2713.08   670.4 2706.82   699.6 2707.55  712.52 2716.22   735.3 2739.09
     758 2748.25   780.8 2779.85   793.7 2791.16   832.7 2808.35   891.2 2827.06
#Mann= 6 ,-1 , 0
       0     .12       0  473.19     .08       0   488.6     .04       0
   540.5     .12       0  652.72    .016       0  712.52     .12       0
#XS Ineff= 2 , 0
           392.8 2691.33
Permanent Ineff=
       F       F
Bank Sta=488.6,540.5
XS Rating Curve= 0 ,0
Exp/Cntr=0.3,0.1

Type RM Length L Ch R = 1 ,32666   ,318.7,316.1,309.6
XS GIS Cut Line= 2
2124467.14291861452803.0957368082124783.74554999453622.041209973
#Sta/Elev= 30
       0 2794.17    89.2 2751.98   117.3  2739.9   145.4 2730.11   215.8 2710.08
   342.4 2687.41     360 2679.44   381.1 2666.42   395.2 2660.59   422.22656.665
   429.6 2655.09   444.4    2655   472.7 2655.06   480.3 2656.29   497.2  2664.2
   511.3 2665.64   528.9 2665.36   553.5 2671.56     564 2676.84   581.6 2682.15
   613.3 2689.22   648.5  2694.7   666.1  2703.5   680.1 2705.02   709.7 2705.34
   743.4 2726.98   773.3 2742.15   813.8 2759.58   855.8 2773.71     878 2785.44
#Mann= 3 , 0 , 0
       0     .12       0   422.2     .04       0   480.3     .12       0
Bank Sta=422.2,480.3
XS Rating Curve= 0 ,0
Exp/Cntr(USF)=0,0
Exp/Cntr=0.3,0.1

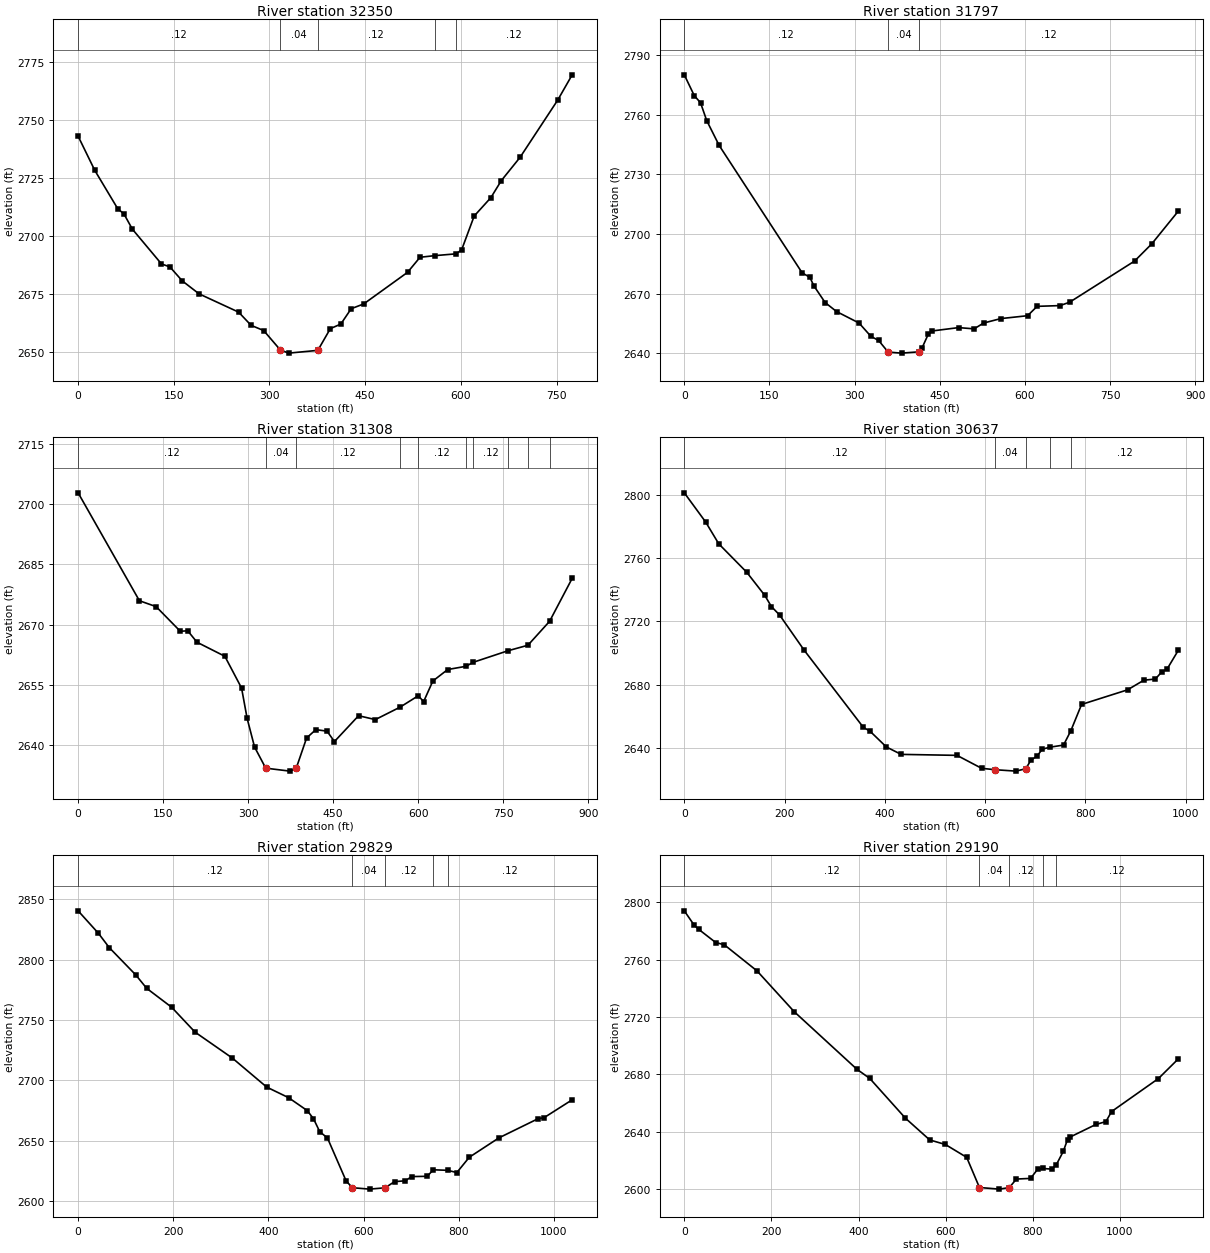
Type RM Length L Ch R = 1 ,32350   ,545,552.3,558.9
XS GIS Cut Line= 2
     2124181.837      453042.804     2124545.284       453726.77
#Sta/Elev= 30
       0 2742.87    26.1 2728.17    62.1 2711.65    71.9 2709.38      85 2702.86
   130.7 2687.87   143.8 2686.62   163.4 2680.55   189.6    2675   251.6 2667.13
   271.2 2661.44   290.9  2659.2     317 2650.84   330.1 2649.48   375.8 2650.67
   395.4 2660.03   411.8 2661.99   428.1  2668.6   447.7 2670.66   516.4 2684.25
     536 2690.75  559.29 2691.45  592.74 2692.23   601.3    2694   620.9  2708.5
   647.1 2716.43   663.4 2723.74   692.8 2733.76   751.7 2758.35   774.5 2769.29
#Mann= 5 ,-1 , 0
       0     .12       0     317     .04       0   375.8     .12       0
  559.29    .016       0  592.74     .12       0
Bank Sta=317,375.8
XS Rating Curve= 0 ,0
Exp/Cntr=0.3,0.1

Type RM Length L Ch R = 1 ,31797   ,491.9,489.2,480.9
XS GIS Cut Line= 2
2123749.51028749453166.1334207882123943.69323473454014.628472882
#Sta/Elev= 30
       0  2780.1    17.6 2769.63    28.6 2766.05    39.5 2757.07    61.4 2744.58
   207.7 2680.43   221.1 2678.25   228.5 2673.82   248.1 2665.53   268.2 2660.99
   307.9  2655.2   328.8 2648.49   342.3 2646.46   359.1 2640.59   382.7 2640.06
     413  2640.7   418.9  2642.7   429.8 2649.55   436.5 2651.21   483.2  2652.9
   510.6 2652.28   527.4 2655.21   557.7 2657.44   604.8 2658.89   621.6  2663.6
     662 2663.98   678.9 2665.69   793.3 2686.39   823.6 2695.05   870.4 2711.54
#Mann= 3 , 0 , 0
       0     .12       0   359.1     .04       0     413     .12       0
Bank Sta=359.1,413
XS Rating Curve= 0 ,0
Exp/Cntr(USF)=0,0
Exp/Cntr=0.3,0.1

Type RM Length L Ch R = 1 ,31308   ,625.9,670.9,694.7
XS GIS Cut Line= 2
     2123271.789      453400.527     2123620.927      454198.965
#Sta/Elev= 30
       0 2702.86   108.1 2675.97   137.6  2674.5   180.2 2668.36   193.3 2668.48
   209.7 2665.63   258.8 2662.13   288.3 2654.21   298.1 2646.65   311.2 2639.52
   330.9 2634.25   373.5 2633.51  384.81 2634.28     403 2641.77   419.3 2643.85
     439 2643.47   452.1 2640.88   494.7 2647.32   524.2 2646.35   567.7 2649.44
  599.94 2652.29   609.4 2650.83   625.7 2655.97   651.9 2658.83  684.11 2659.63
  696.65 2660.62  757.83 2663.49  793.36 2664.88  831.56 2670.84   871.4 2681.54
#Mann= 10 ,-1 , 0
       0     .12       0   330.9     .04       0  384.81     .12       0
   567.7    .016       0  599.94     .12       0  684.11    .016       0
  696.65     .12       0  757.83    .016       0  793.36     .12       0
  831.56    .016       0
Bank Sta=330.9,384.81
XS Rating Curve= 0 ,0
Exp/Cntr=0.3,0.1

Type RM Length L Ch R = 1 ,30637   ,822.9,808.3,788.9
XS GIS Cut Line= 3
     2123045.708      453122.934     2122894.033      453618.022
     2122573.513      453958.575
#Sta/Elev= 30
       0  2801.5    42.6 2783.01    68.8 2769.16   124.5 2751.19   160.6 2736.48
   173.7 2729.45   190.1 2724.08   239.2 2701.72   357.2 2652.86   370.3 2650.49
   403.1 2640.44   432.6 2635.74     544 2635.12     593 2626.93   619.2 2626.04
   661.7 2625.13   681.3 2626.67   691.1 2631.96   704.2 2634.83     714 2639.05
   730.3 2640.35   756.5 2641.64  771.18 2650.81   792.5  2667.4   884.1 2676.64
   916.8 2682.77   939.7 2683.48   952.8 2688.19   962.6 2689.57   985.5 2701.74
#Mann= 5 ,-1 , 0
       0     .12       0   619.2     .04       0   681.3     .12       0
   730.3    .016       0  771.18     .12       0
Bank Sta=619.2,681.3
XS Rating Curve= 0 ,0
Exp/Cntr=0.3,0.1

Type RM Length L Ch R = 1 ,29829   ,650.7,639.3,623.8
XS GIS Cut Line= 2
     2122267.302      452713.698     2122081.286      453735.356
#Sta/Elev= 30
       0 2840.33    42.6 2821.77    65.5 2809.88   121.2  2787.3   144.1 2776.22
   196.6 2760.56   245.7 2740.01   324.3 2718.48   396.4 2694.51   442.2  2685.8
   481.6 2675.07   494.7 2668.35   507.8 2657.67   524.1 2652.38   563.4 2616.81
   576.6 2611.28   612.6 2610.11   645.4 2611.21     665 2616.31   687.9    2617
     701 2620.49   733.8 2620.71  746.48 2626.11   776.5 2625.67     796 2623.83
   822.2 2636.49   884.5 2652.52   966.4 2668.31   979.5 2669.25  1038.4    2684
#Mann= 5 ,-1 , 0
       0     .12       0   576.6     .04       0   645.4     .12       0
  746.48    .016       0   776.5     .12       0
Bank Sta=576.6,645.4
XS Rating Curve= 0 ,0
Exp/Cntr=0.3,0.1

Type RM Length L Ch R = 1 ,29190   ,768.4,778.3,788.9
XS GIS Cut Line= 4
     2121497.482      452659.324     2121503.206      453248.852
      2121557.58      453500.689     2121603.368      453784.006
#Sta/Elev= 30
       0 2793.98    22.9  2783.9    32.8 2781.15    72.1 2771.89    91.7 2770.35
     167 2752.11   252.2 2723.73   396.3 2683.56   425.8 2677.18   507.7 2649.46
   563.4 2634.32   599.3 2631.15   648.3 2622.17   677.6 2601.16   723.3 2600.03
   746.1 2601.09   762.4 2607.05     795 2607.51   811.3 2613.94  823.62 2614.41
   843.9 2613.97  853.77 2616.86     870 2626.31   879.8 2634.55   886.3 2636.42
     945 2645.11   967.9 2647.08   980.9 2654.08  1088.5  2677.1  1134.2 2690.82
#Mann= 5 ,-1 , 0
       0     .12       0   677.6     .04       0   746.1     .12       0
  823.62    .016       0  853.77     .12       0
Bank Sta=677.6,746.1
XS Rating Curve= 0 ,0
Exp/Cntr=0.3,0.1

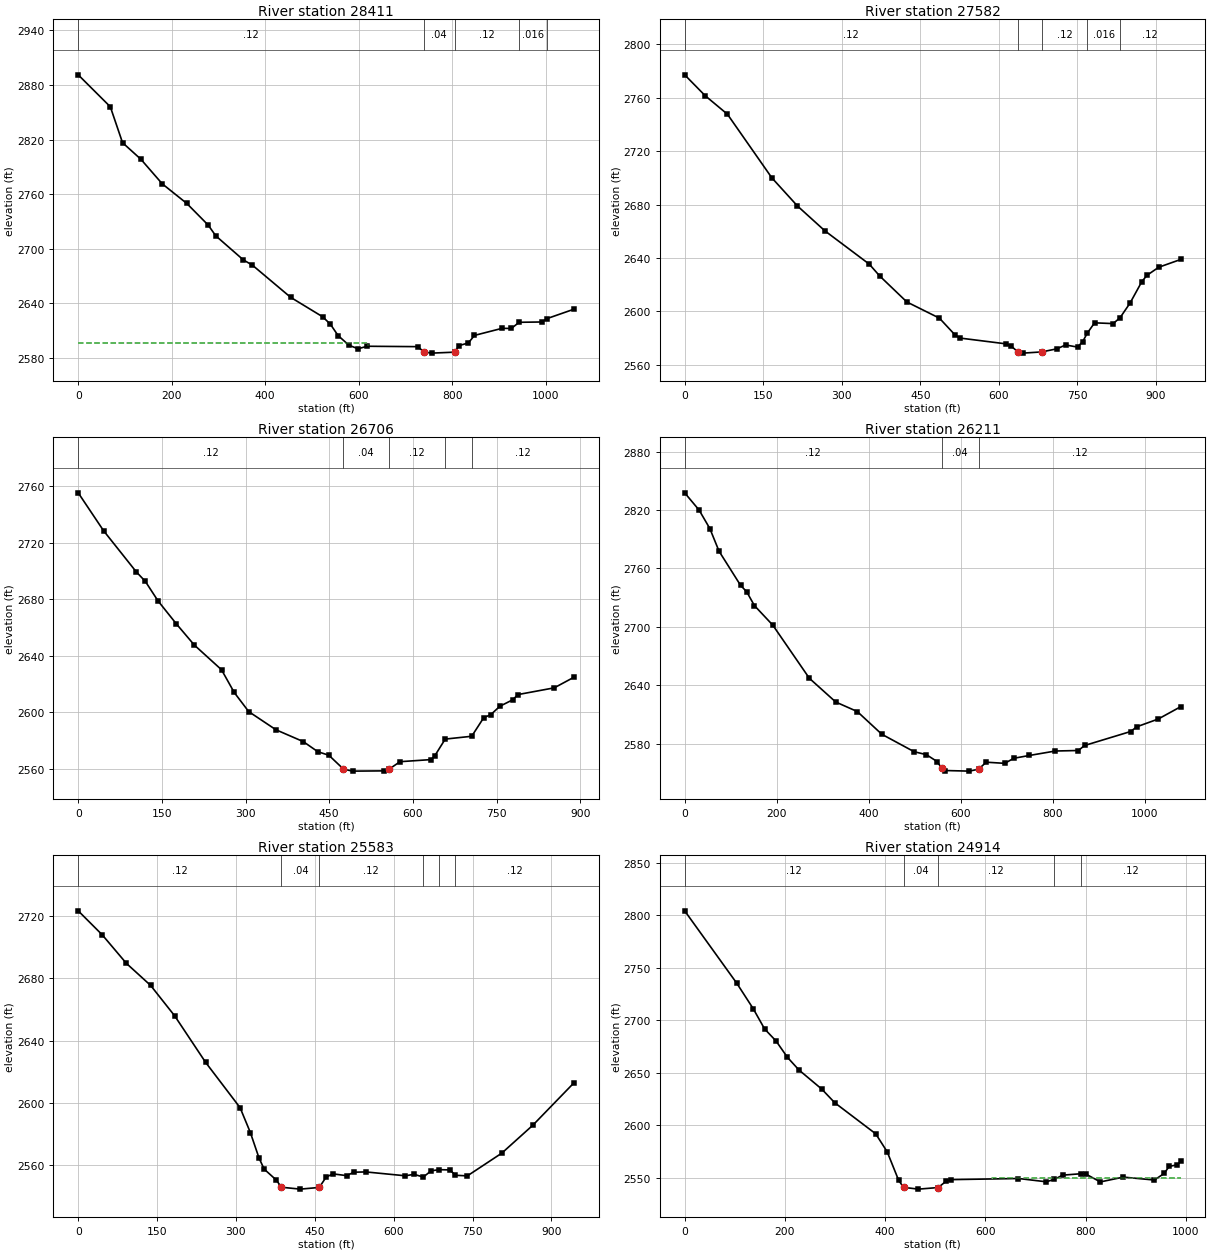
Type RM Length L Ch R = 1 ,28411   ,841.5,829,800.6
XS GIS Cut Line= 3
     2120867.889      452659.324      2120804.93      453211.649
     2120739.109      453712.461
#Sta/Elev= 30
       0 2891.05    68.7 2855.96    94.8 2816.55   134.1 2798.34   179.8 2771.37
   232.2 2749.88     278 2726.12   294.3 2714.28   353.2 2687.88   372.8 2682.02
   454.5 2646.75   523.2 2625.31   539.6 2617.16   555.9 2604.82   578.9 2594.28
   598.5 2590.26   618.2 2593.03   726.5  2592.6   739.6 2586.81     756 2585.49
   805.2 2586.55     815 2593.79   834.7 2596.67   847.8 2604.95   906.9 2612.73
   926.5 2612.55  943.36 2619.35   992.1 2619.69 1002.94  2623.4    1061  2633.8
#Mann= 5 ,-1 , 0
       0     .12       0   739.6     .04       0   805.2     .12       0
  943.36    .016       0 1002.94     .12       0
#XS Ineff= 2 , 0
          619.57 2596.15
Permanent Ineff=
       F       F
Bank Sta=739.6,805.2
XS Rating Curve= 0 ,0
Exp/Cntr=0.3,0.1

Type RM Length L Ch R = 1 ,27582   ,863.1,876.4,885.9
XS GIS Cut Line= 4
     2119869.126      453028.495     2119983.598      453497.827
     2120138.134       453758.25     2120172.475      453915.648
#Sta/Elev= 30
       0 2777.25    39.2 2761.58    81.6 2747.72   166.5 2699.99   215.4 2678.89
   267.7 2660.28   352.5 2635.29   372.1 2626.54   424.3 2606.92   486.4 2594.81
   515.6  2582.5   525.4 2579.89   613.3 2575.55   623.1    2574   636.1 2569.54
   645.9 2568.58   681.7 2569.48     711 2571.83   727.3  2574.7   750.1 2573.13
   759.9 2577.15  768.74 2583.53   782.7  2591.3   818.1 2590.72  831.26 2595.07
   850.4 2606.09   872.9 2622.17   882.6 2626.88   905.1 2632.96     947 2638.79
#Mann= 5 ,-1 , 0
       0     .12       0   636.1     .04       0   681.7     .12       0
  768.74    .016       0  831.26     .12       0
Bank Sta=636.1,681.7
XS Rating Curve= 0 ,0
Exp/Cntr=0.3,0.1

Type RM Length L Ch R = 1 ,26706   ,494.7,495.5,487.1
XS GIS Cut Line= 4
     2119176.574      453297.502      2119233.81      453663.811
      2119250.98      453941.404     2119302.493      454176.071
#Sta/Elev= 30
       0 2755.33    45.5 2728.47   104.1 2699.34   120.3  2692.6   143.1 2678.74
   175.6 2662.65   208.1 2647.49   256.9 2629.98   279.7 2613.87   305.7 2600.32
   354.5 2587.45   403.5 2579.06   429.6  2571.9   449.3 2569.41   475.5  2559.6
   491.8 2558.15   547.4 2558.33   557.3 2559.52   576.9 2564.84   632.5 2566.32
   639.1 2568.92  657.93 2580.85  705.43 2582.85   726.8 2595.91   739.8 2598.24
     756 2604.13   778.7 2608.64   788.5  2612.4   853.4 2617.16   889.1 2624.75
#Mann= 5 ,-1 , 0
       0     .12       0   475.5     .04       0   557.3     .12       0
  657.93    .016       0  705.43     .12       0
Bank Sta=475.5,557.3
XS Rating Curve= 0 ,0
Exp/Cntr=0.3,0.1

Type RM Length L Ch R = 1 ,26211   ,624.5,627.4,622.3
XS GIS Cut Line= 2
2118650.09723808453259.0035259932118848.50155375454318.566999006
#Sta/Elev= 30
       0 2837.63    31.4 2819.88    54.7 2800.92    74.7 2777.64   121.5 2742.58
   134.8 2735.99   151.5 2721.82   191.6 2701.65   271.1 2647.05   328.4  2622.7
   375.2 2612.93   428.5 2589.59   498.8 2571.64   525.4 2568.64   548.7 2561.54
   558.7 2554.65   565.4 2552.34   618.8 2551.71   638.8 2553.71   655.5 2560.89
   695.8  2559.7   715.3  2564.9     749 2567.78   805.7 2572.38   855.8  2572.9
   869.2 2578.04   969.3 2592.41   982.6 2597.25  1029.4 2605.26    1078 2617.86
#Mann= 3 , 0 , 0
       0     .12       0   558.7     .04       0   638.8     .12       0
Bank Sta=558.7,638.8
XS Rating Curve= 0 ,0
Exp/Cntr(USF)=0,0
Exp/Cntr=0.3,0.1

Type RM Length L Ch R = 1 ,25583   ,682,668.9,646
XS GIS Cut Line= 2
     2118051.892       453549.34     2118277.973      454465.111
#Sta/Elev= 30
       0 2723.23    45.8  2707.8    91.7 2689.53   137.6 2675.46   183.4 2655.95
   242.4 2626.06   307.9 2597.04   327.5 2581.05   343.9 2564.78   353.7 2557.66
   376.6 2550.72   386.5 2546.05   422.5 2544.84   458.5 2545.92   471.6 2552.57
   484.7 2554.62   510.9 2553.47     524 2555.68     547 2555.87   622.3 2553.39
   638.7 2554.33  656.34 2552.58   671.4 2556.59  686.76 2557.31   707.4 2557.15
  717.18 2553.72   740.2 2553.34   805.7 2567.91   864.7  2585.8   943.3 2613.11
#Mann= 6 ,-1 , 0
       0     .12       0   386.5     .04       0   458.5     .12       0
  656.34     .08       0  686.76    .016       0  717.18     .12       0
Bank Sta=386.5,458.5
XS Rating Curve= 0 ,0
Exp/Cntr=0.3,0.1

Type RM Length L Ch R = 1 ,24914   ,249.7,229.8,201.1
XS GIS Cut Line= 4
     2117253.454      453763.973     2117445.194      454058.737
     2117576.836      454196.103     2117948.868      454445.078
#Sta/Elev= 30
       0 2804.12   104.2 2734.97   136.8 2710.87   159.5 2691.58   182.3 2680.13
   205.1 2664.53   227.9 2652.56   273.5 2634.31   299.5 2621.28   381.2  2591.7
   404.1 2574.56   427.1 2547.23   436.9 2540.69   466.4 2539.01   505.8 2540.51
   522.2 2546.76   532.1 2548.06   666.1 2549.13   721.6    2546  737.15 2548.22
   754.3 2552.33  790.25 2553.65     800  2553.5   829.4 2545.87   875.2 2550.46
   937.3 2547.66   956.9    2554   966.7 2560.62     983 2562.21   989.6 2565.35
#Mann= 5 ,-1 , 0
       0     .12       0   436.9     .04       0   505.8     .12       0
  737.15    .016       0  790.25     .12       0
#XS Ineff= 2 , 0
                          613.04         2549.14
Permanent Ineff=
       F       F
Bank Sta=436.9,505.8
XS Rating Curve= 0 ,0
Exp/Cntr=0.5,0.3

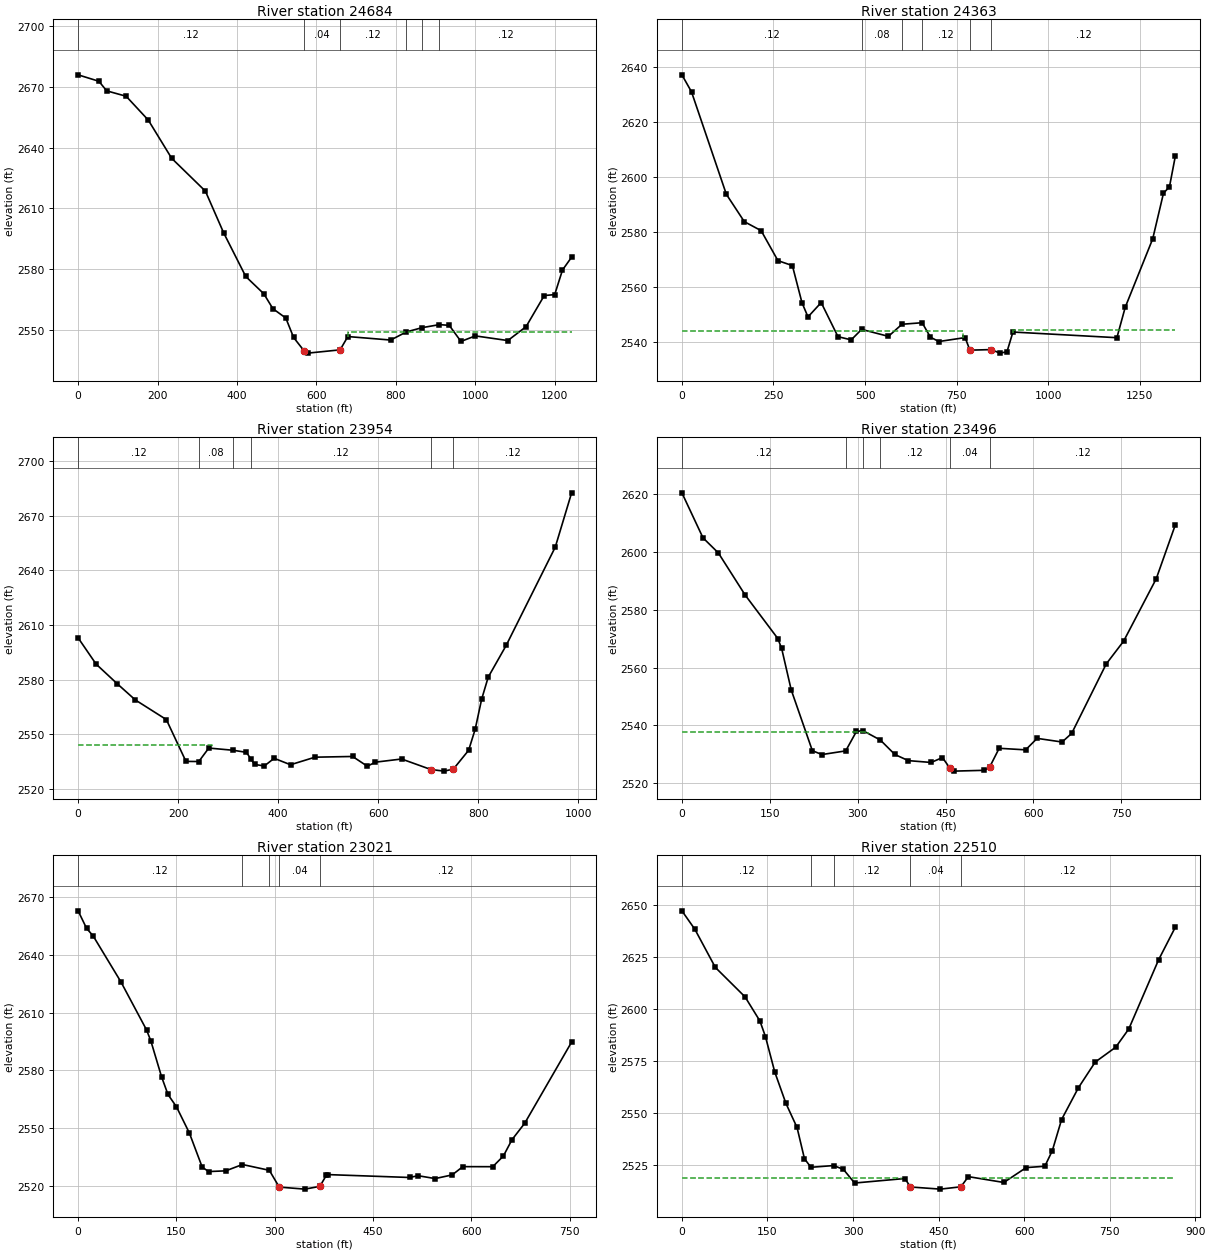
Type RM Length L Ch R = 1 ,24684   ,307.5,321.3,338.6
XS GIS Cut Line= 4
     2116915.763       453869.86     2117167.601      454224.721
     2117450.917      454299.127     2117931.697      454482.282
#Sta/Elev= 30
       0 2676.03    52.4 2672.84      72 2668.11     121 2665.44   176.7 2653.66
   235.6 2634.77   320.6 2618.51   366.4 2597.95   422.1 2576.34   467.7 2567.76
   490.5  2560.4     523 2555.79   542.6 2546.18   568.6 2539.66   578.4 2538.44
   659.7 2540.06   679.2 2546.63     787 2544.91  826.67 2548.93   865.7 2551.01
  909.64 2552.53   934.5 2552.17     964 2544.22  1000.1 2546.96    1082 2544.66
  1127.9 2551.52  1173.7 2566.91    1200 2567.37  1219.6 2579.54  1242.6 2585.88
#Mann= 6 ,-1 , 0
       0     .12       0   568.6     .04       0   659.7     .12       0
  826.67     .08       0   865.7    .016       0  909.64     .12       0
#XS Ineff= 2 , 0
                             680         2548.83
Permanent Ineff=
       F       F
Bank Sta=568.6,659.7
XS Rating Curve= 0 ,0
Exp/Cntr=0.5,0.3

Type RM Length L Ch R = 1 ,24363   ,394.6,409.6,438.4
XS GIS Cut Line= 4
      2116397.78      454041.567     2116978.723      454410.737
     2117187.633      454525.208     2117542.495      454751.289
#Sta/Elev= 30
       0 2637.32    26.2 2631.13   121.3 2593.83   170.4 2583.86   216.3 2580.58
   262.2 2569.66   301.6 2567.86   327.8 2554.35   344.2 2549.17   380.2  2554.4
   426.1 2541.98   462.2 2540.82  490.61 2544.63   563.8  2542.1  600.75  2546.5
  655.82 2547.06   678.5 2541.79   701.4 2540.21   773.2 2541.65   786.2 2537.07
     845 2537.28   867.8 2535.99   887.4 2536.46   903.7 2543.67  1187.5 2541.61
  1210.3  2552.7  1285.3 2577.61  1314.7 2594.24    1331 2596.54  1347.3  2607.9
#Mann= 6 ,-1 , 0
       0     .12       0  490.61     .08       0  600.75    .016       0
  655.82     .12       0   786.2     .04       0     845     .12       0
#XS Ineff= 2 , 0
          767.04 2543.92  902.67         2544.31
Permanent Ineff=
       F       F
Bank Sta=786.2,845
XS Rating Curve= 0 ,0
Exp/Cntr=0.5,0.3

Type RM Length L Ch R = 1 ,23954   ,464.5,457.2,457.8
XS GIS Cut Line= 4
     2116449.292      454098.802     2116778.398      454636.818
      2116798.43      454828.558     2116786.983      454991.679
#Sta/Elev= 30
       0 2602.95      36  2588.5    78.4 2577.65   114.4  2568.8   176.5 2557.98
   215.7 2534.98  241.37 2534.91   261.4 2542.32  310.62 2541.09   336.6 2539.96
  345.24 2536.45   352.9 2533.31   372.5 2532.47   392.1 2536.68   424.8 2533.14
   473.8  2537.3     549 2537.69   578.4 2532.33   594.7 2534.56     647  2536.3
   705.8 2530.49     732 2529.63  750.53 2530.75     781 2541.07   794.1 2552.63
   807.1 2569.22   820.2 2581.32   856.2 2598.81   954.3 2652.84     987  2682.7
#Mann= 6 ,-1 , 0
       0     .12       0  241.37     .08       0  310.62    .016       0
  345.24     .12       0   705.8     .04       0  750.53     .12       0
#XS Ineff= 2 , 0
          267.39 2543.73
Permanent Ineff=
       F       F
Bank Sta=705.8,750.53
XS Rating Curve= 0 ,0
Exp/Cntr=0.3,0.1

Type RM Length L Ch R = 1 ,23496   ,502,475.6,458.5
XS GIS Cut Line= 4
     2116386.333      454084.493     2116366.301      454496.591
     2116369.162      454674.021     2116386.333      454925.858
#Sta/Elev= 30
       0 2620.54      36 2604.95    62.2 2599.73   108.1  2585.1   163.7 2570.08
   170.3 2566.62   186.6 2552.28   222.7 2531.22     239 2529.88  279.61 2531.15
     298 2537.91  309.18 2538.15  338.76 2534.91   363.5 2529.91   386.4 2527.78
   425.5 2527.14   444.8 2528.84   457.8 2525.07   464.2 2524.14   515.8 2524.42
   525.5  2525.6   541.6 2532.05   586.8 2531.51   606.4 2535.49     649 2534.22
   665.4 2537.21   724.4 2561.28     754 2569.14   809.7 2590.76   842.5 2609.55
#Mann= 6 ,-1 , 0
       0     .12       0  279.61     .08       0  309.18    .016       0
  338.76     .12       0   457.8     .04       0   525.5     .12       0
#XS Ineff= 2 , 0
          318.26 2537.64
Permanent Ineff=
       F       F
Bank Sta=457.8,525.5
XS Rating Curve= 0 ,0
Exp/Cntr=0.3,0.1

Type RM Length L Ch R = 1 ,23021   ,524.2,510.6,507.2
XS GIS Cut Line= 3
     2115736.708      454508.038      2116028.61      454811.387
     2116263.276      455046.053
#Sta/Elev= 30
       0 2663.03      13 2653.88    22.8 2650.06    65.3 2626.08   104.4 2601.08
     111 2595.32   127.3 2576.71   137.1 2567.48   150.1 2561.04   169.7 2547.47
   189.3 2529.69   199.1 2527.38   225.2 2527.75  250.69 2531.05  291.68 2528.03
   306.8  2519.3   345.9 2518.24   368.8 2519.67   378.6 2525.42   381.8 2525.79
   505.6  2524.3   518.6 2525.22   544.6 2523.73   570.6 2525.64   586.9 2529.94
   632.5 2529.91   648.7 2535.46   661.8 2543.94   681.3 2552.54   752.8 2594.76
#Mann= 5 ,-1 , 0
       0     .12       0  250.69    .016       0  291.68     .12       0
   306.8     .04       0   368.8     .12       0
#XS Ineff= 2 , 0
                          520.07         2524.87
Permanent Ineff=
       F       F
Bank Sta=306.8,368.8
XS Rating Curve= 0 ,0
Exp/Cntr=0.3,0.1

Type RM Length L Ch R = 1 ,22510   ,572.6,615.3,656.2
XS GIS Cut Line= 4
     2115433.359      454943.029     2115690.919      455177.696
      2115868.35      455269.273     2116174.561      455352.264
#Sta/Elev= 30
       0  2647.3    22.8  2638.4    58.6 2620.12   110.7 2605.96   136.8 2594.37
   146.5 2586.86   162.8 2569.87   182.4 2554.76   201.9 2543.18   214.9 2528.18
  226.25 2524.05  266.21 2524.89   283.3 2523.02   302.8 2516.49     391 2518.66
   400.8 2514.59   453.2 2513.56   489.2 2514.68   502.3 2519.56   564.5 2516.76
   603.7 2523.91   636.4 2524.55   649.5 2532.02   665.8 2547.02   695.3 2562.29
   724.7 2574.61   760.7 2581.77   783.6 2590.52   835.9 2623.78   865.4 2639.53
#Mann= 5 ,-1 , 0
       0     .12       0  226.25    .016       0  266.21     .12       0
   400.8     .04       0   489.2     .12       0
#XS Ineff= 2 , 0
          383.57  2518.7  526.08         2518.82
Permanent Ineff=
       F       F
Bank Sta=400.8,489.2
XS Rating Curve= 0 ,0
Exp/Cntr=0.3,0.1