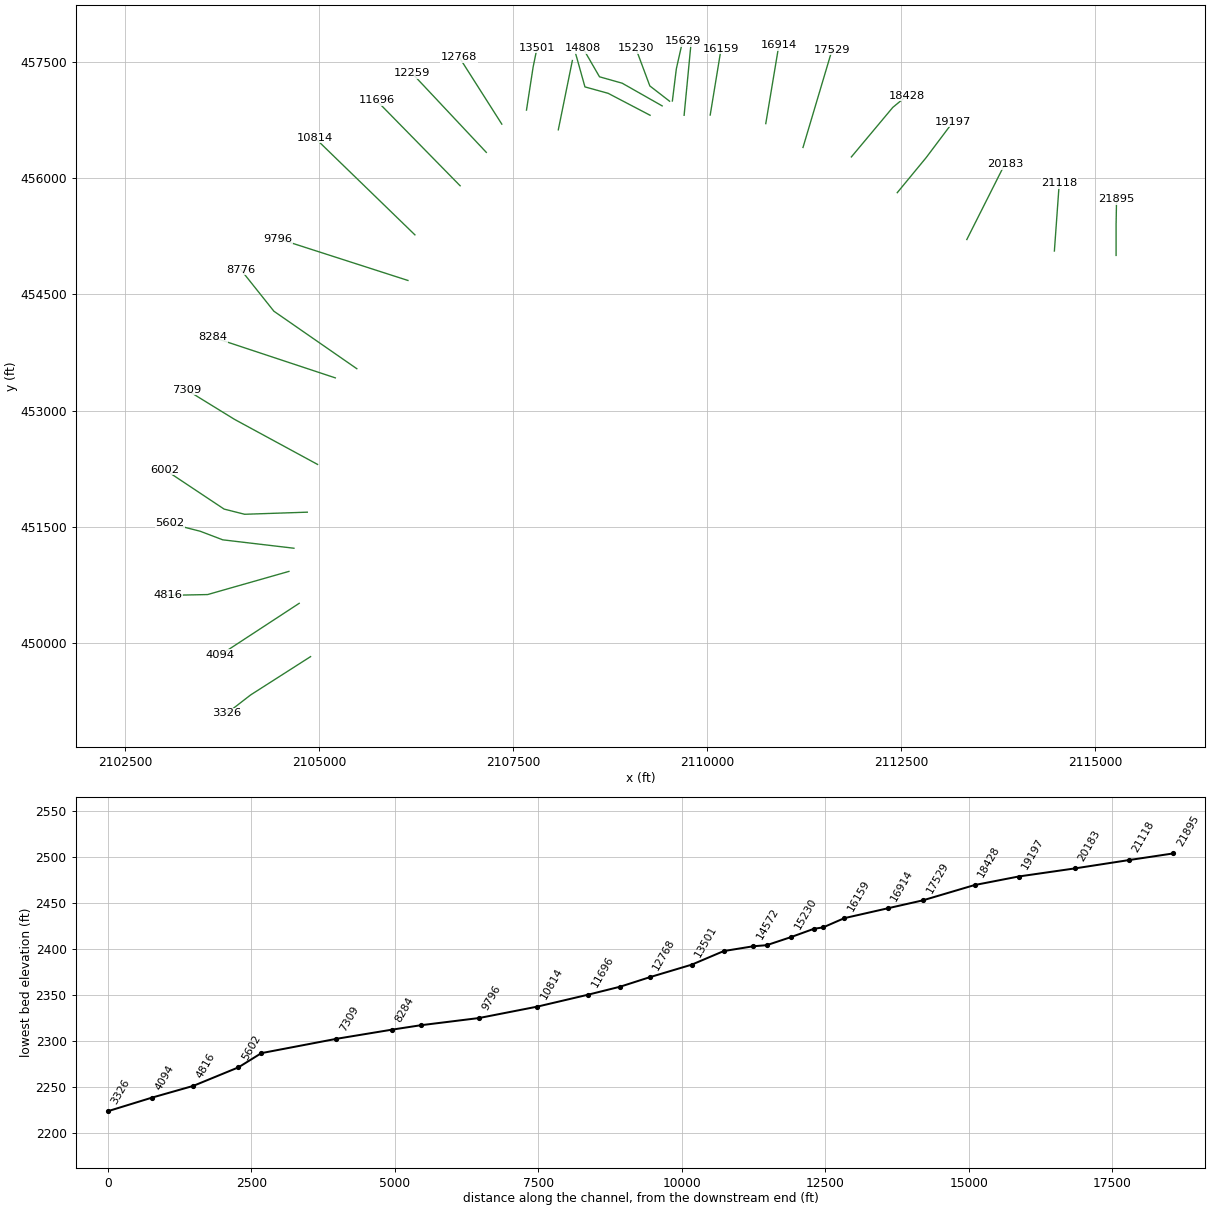
HEC-RAS study NFKCHERRYRV.prj: NFKCHERRYRV

--- NFKCHERRYRV.g01 (geometry) --- (continued)

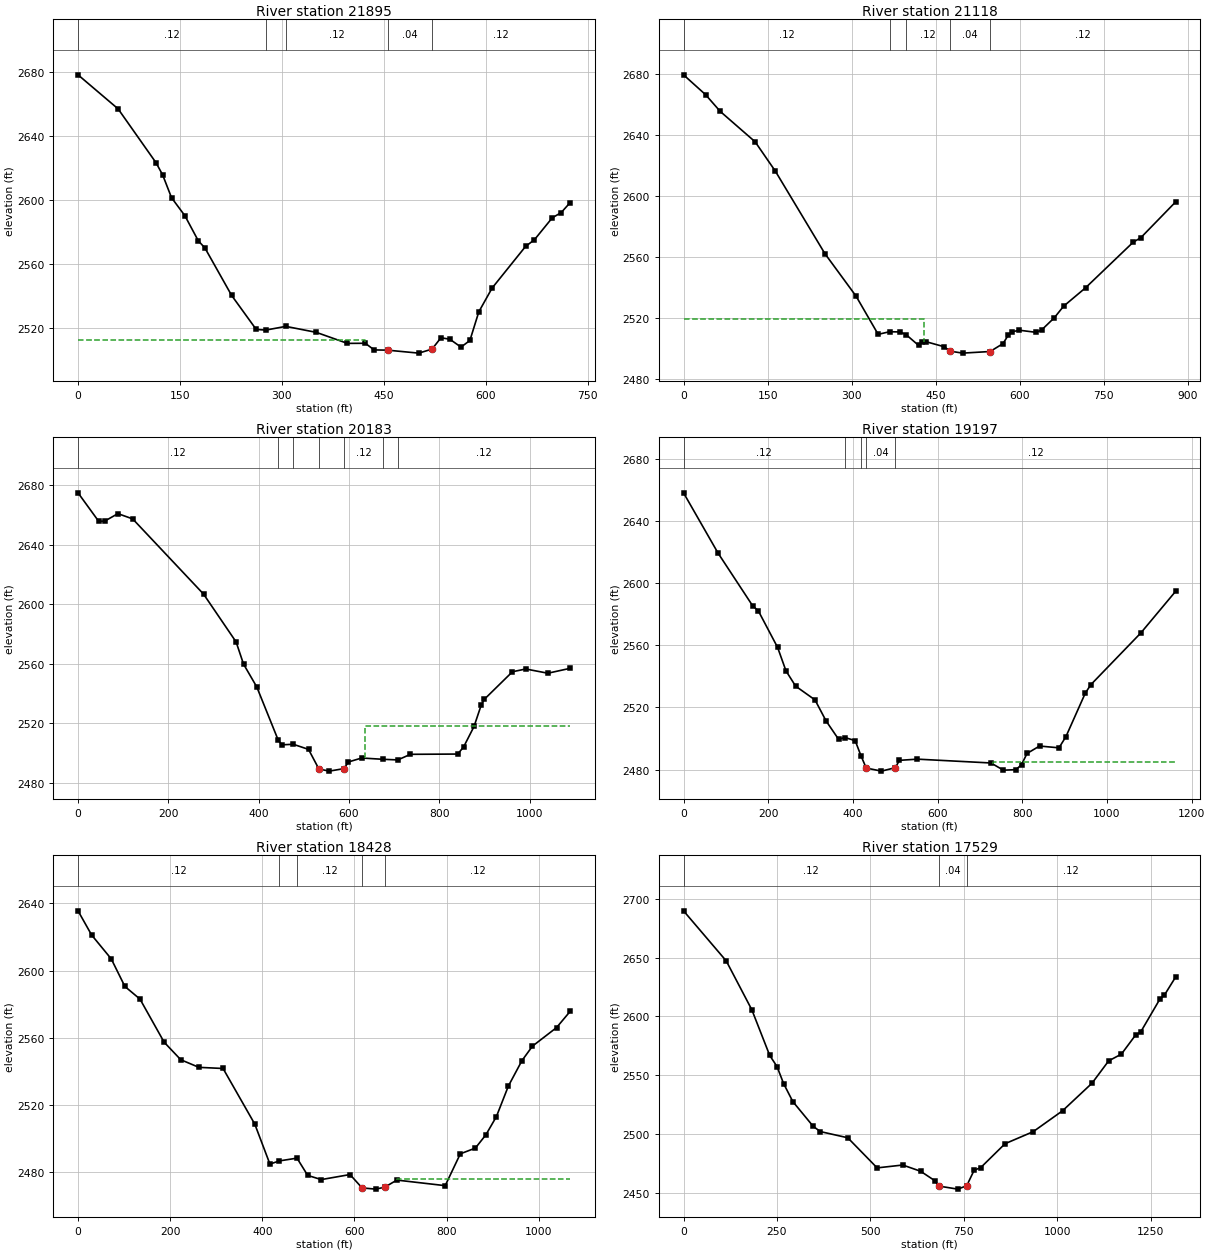
Type RM Length L Ch R = 1 ,21895   ,776.1,776.7,772.8
XS GIS Cut Line= 3
     2115273.099      455003.127     2115273.099        455409.5
     2115278.822      455727.158
#Sta/Elev= 30
       0 2678.46      59 2657.13   114.7 2623.47   124.5 2615.85   137.6 2601.52
   157.3 2590.21     177 2574.52   186.8    2570   226.1 2540.28   262.2 2519.02
  276.29  2518.6  305.82 2520.92   350.7 2517.17   396.5 2510.27   422.8 2510.34
   435.8 2506.18   455.5 2506.03   501.4 2504.17     521 2506.68   534.1  2513.8
   547.2 2512.87   563.6 2507.94   576.7 2512.09   589.8 2530.02   609.4 2544.93
   658.6 2570.98   671.7  2575.2   697.9 2588.91     711 2592.17   724.1 2598.38
#Mann= 5 ,-1 , 0
       0     .12       0  276.29    .016       0  305.82     .12       0
   455.5     .04       0     521     .12       0
#XS Ineff= 2 , 0
          422.18 2512.53
Permanent Ineff=
       F       F
Bank Sta=455.5,521
XS Rating Curve= 0 ,0
Exp/Cntr=0.3,0.1

Type RM Length L Ch R = 1 ,21118   ,945.5,935.3,922.5
XS GIS Cut Line= 2
     2114477.522      455060.362     2114540.482      455936.069
#Sta/Elev= 30
       0 2679.27    39.3 2666.28    65.5  2655.3   127.8 2635.37   163.8 2616.18
   252.2 2562.13   307.9 2534.22   347.3  2509.2  367.69 2510.92   386.6 2510.78
   397.3 2508.96   419.3 2502.02   425.9 2504.14   432.4 2504.42   465.2 2501.08
     475 2498.23     498  2496.9   547.1 2497.96     570 2503.12   579.8 2508.84
   586.4 2510.92   599.5  2511.9     629 2510.53   638.8 2512.01   661.8 2520.14
   678.1 2527.61   717.4 2539.72   802.6 2569.68   815.7 2572.43     878 2595.95
#Mann= 5 ,-1 , 0
       0     .12       0  367.69    .016       0   397.3     .12       0
     475     .04       0   547.1     .12       0
#XS Ineff= 2 , 0
          428.82 2519.33
Permanent Ineff=
       F       F
Bank Sta=475,547.1
XS Rating Curve= 0 ,0
Exp/Cntr=0.3,0.1

Type RM Length L Ch R = 1 ,20183   ,986.6,985.8,971.1
XS GIS Cut Line= 2
     2113349.025      455208.221     2113838.708      456181.228
#Sta/Elev= 30
       0 2674.71    45.8 2655.57    58.9 2655.69    88.3 2660.74     121 2657.21
     278 2606.69     350 2574.59   366.4 2559.74   395.8 2544.36  443.44  2508.5
   451.4 2505.53  476.51  2505.9   510.3 2502.47   533.2 2489.32   556.1 2487.87
   588.8 2489.55   598.6 2494.02     628 2496.68   674.9 2495.81  707.97  2495.4
     736 2499.16   840.7 2499.33   853.8  2504.2   876.7 2517.84     893 2532.57
   899.6 2536.12   961.7 2554.58   991.2 2556.44  1040.2  2553.6  1089.3 2556.88
#Mann= 7 ,-1 , 0
       0     .12       0  443.44    .016       0  476.51     .12       0
   533.2     .04       0   588.8     .12       0   674.9    .016       0
  707.97     .12       0
#XS Ineff= 2 , 0
                          636.02         2518.43
Permanent Ineff=
       F       F
Bank Sta=533.2,588.8
XS Rating Curve= 0 ,0
Exp/Cntr=0.3,0.1

Type RM Length L Ch R = 1 ,19197   ,773,768.6,767.3
XS GIS Cut Line= 3
     2112452.332      455812.376     2112824.364      456263.902
     2113170.958      456724.968
#Sta/Elev= 30
       0    2658    81.7 2619.16   163.4 2585.28   176.5 2582.15   222.2 2558.55
   241.9 2543.51   264.7 2533.67   310.5 2524.81   336.6  2511.3   366.1 2499.51
  381.04 2500.61   405.3 2498.64  419.31  2488.7   431.4    2481   467.4 2479.01
   500.1 2481.23   509.9 2485.95   552.4 2486.71     726 2484.25   755.5  2479.6
     785 2479.97   798.1 2483.18   811.2 2490.39   840.7 2495.15   886.6 2493.99
     903  2501.2   948.8 2529.22   961.9 2534.63  1079.9 2567.89  1161.9 2594.61
#Mann= 5 ,-1 , 0
       0     .12       0  381.04    .016       0  419.31     .12       0
   431.4     .04       0   500.1     .12       0
#XS Ineff= 2 , 0
                          730.48         2484.78
Permanent Ineff=
       F       F
Bank Sta=431.4,500.1
XS Rating Curve= 0 ,0
Exp/Cntr=0.3,0.1

Type RM Length L Ch R = 1 ,18428   ,893.7,899.7,913.9
XS GIS Cut Line= 3
     2111860.896      456273.441     2112395.096      456912.573
     2112576.343      457062.022
#Sta/Elev= 30
       0 2635.59    29.5 2621.19    72.2 2606.91   101.7  2590.5   134.5 2582.97
   186.9 2557.28     223 2546.82   262.4 2542.28   314.8  2541.6   383.7 2508.41
   416.5  2484.6  436.79  2486.5  475.28 2488.15   498.5 2477.86     528 2475.37
   590.3 2478.37   616.5 2470.41     646 2469.68   665.7 2470.85     692 2475.07
   796.9 2471.75   829.7 2490.72   862.4 2494.15   885.2 2502.06     908  2512.9
   934.1 2531.18   963.5  2546.3   986.3 2554.92  1038.5 2565.97  1067.9 2575.58
#Mann= 5 ,-1 , 0
       0     .12       0  436.79    .016       0  475.28     .12       0
   616.5     .04       0   665.7     .12       0
#XS Ineff= 2 , 0
                          692.97         2475.77
Permanent Ineff=
       F       F
Bank Sta=616.5,665.7
XS Rating Curve= 0 ,0
Exp/Cntr=0.3,0.1

Type RM Length L Ch R = 1 ,17529   ,611.1,615,620.2
XS GIS Cut Line= 2
2111237.37429541456395.4802608472111613.07608465457657.669417942
#Sta/Elev= 30
       0 2689.93   114.3  2647.3   182.8 2605.71   230.7 2566.82   250.2  2557.4
   267.8 2542.92   292.5 2527.57   347.1 2506.48   366.2 2502.02   439.5 2496.77
   518.2 2471.12   586.7 2473.56   634.6 2468.24   672.3 2460.27   683.5 2455.62
   733.9 2453.04   757.9 2455.89   777.7 2469.06   795.5 2471.39   860.5 2491.69
   935.9 2501.96  1014.6 2519.78  1093.3 2543.21  1137.8  2562.2    1172 2567.99
  1209.7 2584.11  1223.4 2586.72  1274.7 2614.68  1286.9 2618.11  1316.9 2633.51
#Mann= 3 , 0 , 0
       0     .12       0   683.5     .04       0   757.9     .12       0
Bank Sta=683.5,757.9
XS Rating Curve= 0 ,0
Exp/Cntr(USF)=0,0
Exp/Cntr=0.3,0.1

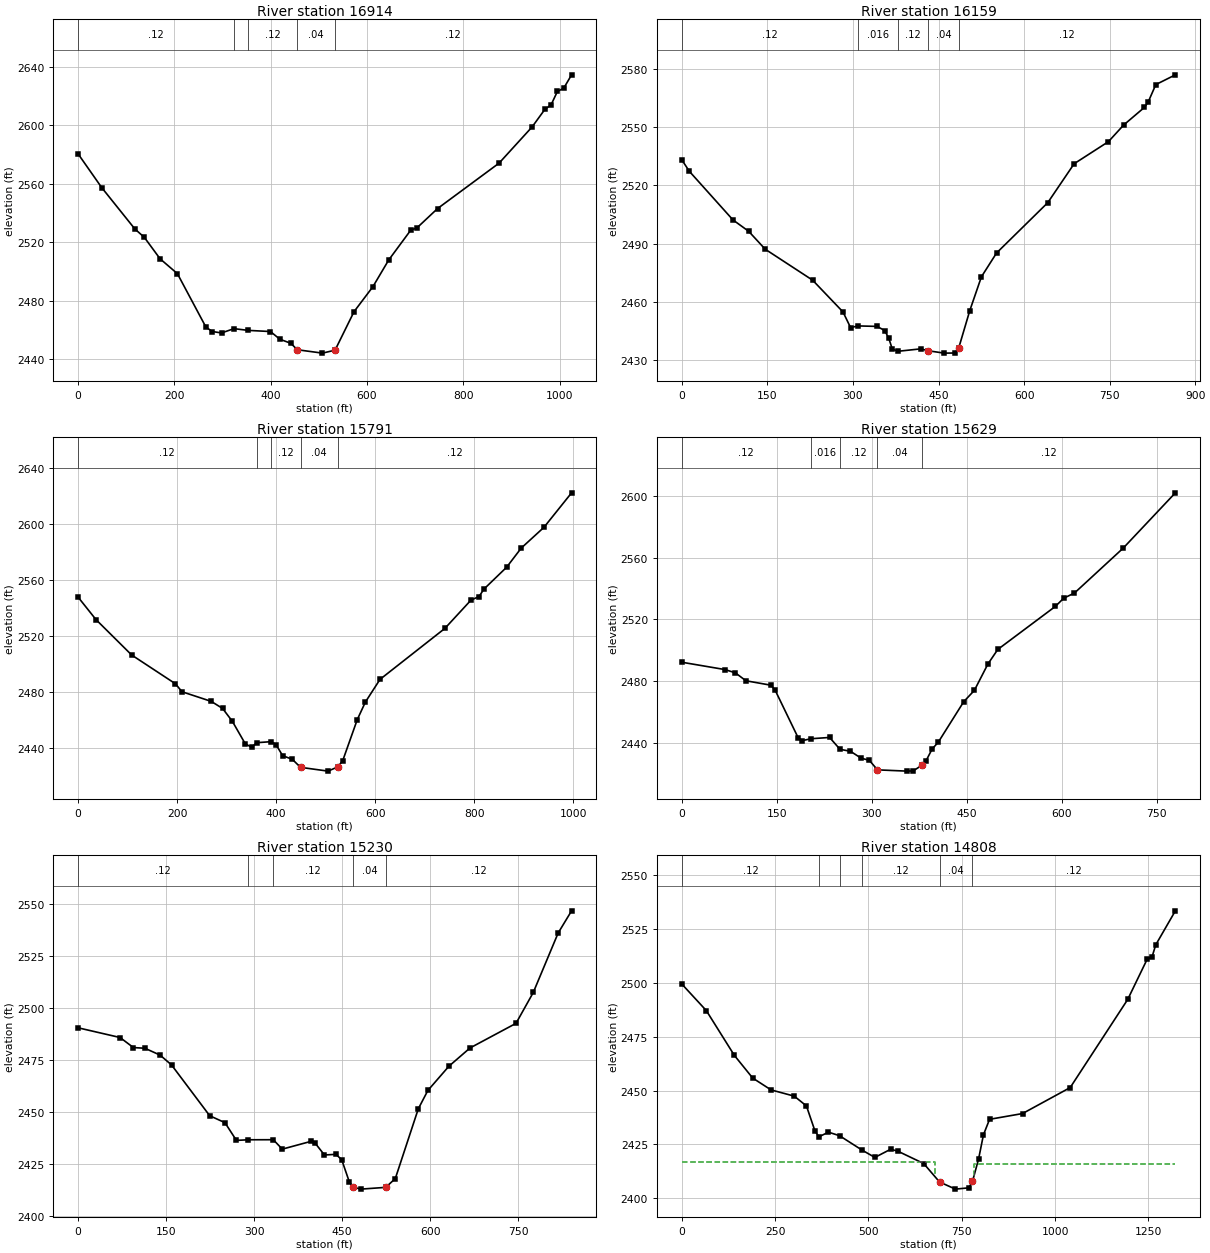
Type RM Length L Ch R = 1 ,16914   ,748.4,754.3,751.8
XS GIS Cut Line= 2
     2110757.519      456702.709     2110926.046      457713.873
#Sta/Elev= 30
       0 2580.57    49.1 2557.49   117.9 2529.23   137.6 2523.49   170.3 2508.82
   206.3 2498.66   265.3 2462.26   278.4 2459.11     298 2458.14   323.8 2461.06
  353.74 2459.87   399.6 2459.09   419.2 2453.81   442.1 2451.04   455.2 2446.65
   507.6 2444.33   533.8 2446.36   573.2 2472.68   612.4 2489.76   645.2    2508
     691 2528.41   704.2 2530.06   746.7 2543.18   874.5 2574.24   943.2 2599.04
   969.4 2610.91   982.5 2614.09   995.6 2623.25  1008.7 2625.44  1025.1 2634.61
#Mann= 5 ,-1 , 0
       0     .12       0   323.8    .016       0  353.74     .12       0
   455.2     .04       0   533.8     .12       0
Bank Sta=455.2,533.8
XS Rating Curve= 0 ,0
Exp/Cntr=0.3,0.1

Type RM Length L Ch R = 1 ,16159   ,366,368.4,368.8
XS GIS Cut Line= 2
2110041.17784567  456813.58821852110181.36144224457667.433761271
#Sta/Elev= 30
       0  2533.1    13.1 2527.24    89.6  2502.2   117.1 2496.36   146.1 2487.13
   229.3 2471.17   282.5 2454.83   295.8 2446.77   309.1 2447.63   342.3 2447.38
   355.6 2445.25   362.7 2441.36   368.9 2435.74   378.9 2434.57   418.8 2435.82
   432.1 2434.83   459.8 2433.62   478.6 2433.68   485.5 2436.35   504.8 2455.49
   525.2 2472.91   551.8 2485.19   641.5 2511.07   687.8 2531.13   747.9  2542.5
   774.5 2551.03   811.1 2560.17   817.7 2562.97     831 2571.88   865.3 2576.91
#Mann= 5 ,-1 , 0
       0     .12       0   309.1    .016       0   378.9     .12       0
   432.1     .04       0   485.5     .12       0
Bank Sta=432.1,485.5
XS Rating Curve= 0 ,0
Exp/Cntr(USF)=0,0
Exp/Cntr=0.3,0.1

Type RM Length L Ch R = 1 ,15791   ,162.6,161.5,159.9
XS GIS Cut Line= 2
     2109705.018      456810.821     2109800.411      457802.907
#Sta/Elev= 30
       0 2547.96    36.1 2531.91   108.2 2506.59   196.7    2486   209.8 2480.33
   268.8 2473.45   291.8  2468.4   311.5 2459.21   337.7 2443.07   350.8 2440.59
  360.63  2443.9   390.3 2444.65     400 2442.36   413.1 2434.66   432.8 2431.98
   449.2 2426.29   504.9 2423.58   524.6 2426.63   534.4    2431   563.9 2460.45
   580.3 2472.99   609.8 2489.18   740.9 2525.63   793.4 2545.78   809.8 2548.38
   819.6 2553.67   865.5 2569.33     895 2583.01   940.9 2597.86   996.7 2622.51
#Mann= 5 ,-1 , 0
       0     .12       0  360.63    .016       0   390.3     .12       0
   449.2     .04       0   524.6     .12       0
Bank Sta=449.2,524.6
XS Rating Curve= 0 ,0
Exp/Cntr=0.3,0.1

Type RM Length L Ch R = 1 ,15629   ,383.7,399.4,411.2
XS GIS Cut Line= 3
2109553.72124849 456995.189695882109604.69710179457409.368503941
2109684.34687257457763.013486208
#Sta/Elev= 30
       0 2492.35    68.1 2487.62    84.6  2485.5   101.2 2480.39   140.8 2477.52
   147.4 2474.29   183.8 2443.53   190.4 2441.73   203.7 2442.94   233.4 2443.78
   249.9 2436.11   266.4 2434.84   283.2 2430.41   296.2 2429.01   309.12422.848
   355.7 2422.03   365.6 2422.19   379.3 2425.83   385.4 2428.37   395.4 2436.27
   405.3 2440.81   445.4 2466.89   462.2 2474.19   483.6 2491.22   499.2 2500.62
     590 2528.36   603.5 2533.76   620.3 2537.03   697.6 2566.15   779.8 2601.77
#Mann= 5 ,-1 , 0
       0     .12       0   203.7    .016       0   249.9     .12       0
   309.1     .04       0   379.3     .12       0
Bank Sta=309.1,379.3
XS Rating Curve= 0 ,0
Exp/Cntr(USF)=0,0
Exp/Cntr=0.3,0.1

Type RM Length L Ch R = 1 ,15230   ,409.8,422.2,486.8
XS GIS Cut Line= 3
     2109517.412      456992.068     2109263.031      457189.213
     2109081.785      457675.716
#Sta/Elev= 30
       0 2490.55    71.5 2485.88    94.3 2481.04   113.8 2480.72   139.8 2477.41
   159.3 2472.67   224.3 2448.27   250.3 2444.93   269.8 2436.41  290.13 2436.71
  332.63 2436.74     348 2432.21   396.9 2435.95   403.5 2435.26   419.8  2429.4
   439.4  2429.7   449.2 2427.15   462.2 2416.47   468.8 2413.94   481.8 2412.98
   524.3 2413.83   540.6 2418.07   579.8 2451.62   596.1 2460.43     632 2472.09
   667.9 2480.85   746.3 2492.69   775.7 2507.54   818.1 2536.13     841 2546.79
#Mann= 5 ,-1 , 0
       0     .12       0  290.13    .016       0  332.63     .12       0
   468.8     .04       0   524.3     .12       0
Bank Sta=468.8,524.3
XS Rating Curve= 0 ,0
Exp/Cntr=0.5,0.3

Type RM Length L Ch R = 1 ,14808   ,221.8,236.4,228.5
XS GIS Cut Line= 4
     2109422.019      456931.652     2108906.898       457224.19
      2108614.36      457306.864     2108401.316      457675.716
#Sta/Elev= 30
       0 2499.51    65.5 2487.19   140.7 2466.36   189.8 2455.83   238.9 2450.33
   301.1 2447.43   333.8 2442.87   356.7 2431.19  367.33 2428.53   392.8 2430.68
  422.43 2429.04  482.25  2422.4   517.1 2418.94   559.7 2422.76   579.3 2421.79
     648  2416.1   690.5 2407.52     733  2404.2   768.8  2404.8   778.7 2407.78
   795.1 2418.21   808.1 2429.45   824.5 2436.65   912.8 2439.33  1040.6 2451.41
  1194.6 2492.35    1247 2511.14  1260.1  2512.3  1269.9 2517.78  1322.4 2533.57
#Mann= 6 ,-1 , 0
       0     .12       0  367.33     .08       0  422.43    .016       0
  482.25     .12       0   690.5     .04       0   778.7     .12       0
#XS Ineff= 2 , 0
          677.58 2417.03  783.03         2416.08
Permanent Ineff=
       F       F
Bank Sta=690.5,778.7
XS Rating Curve= 0 ,0
Exp/Cntr=0.5,0.3

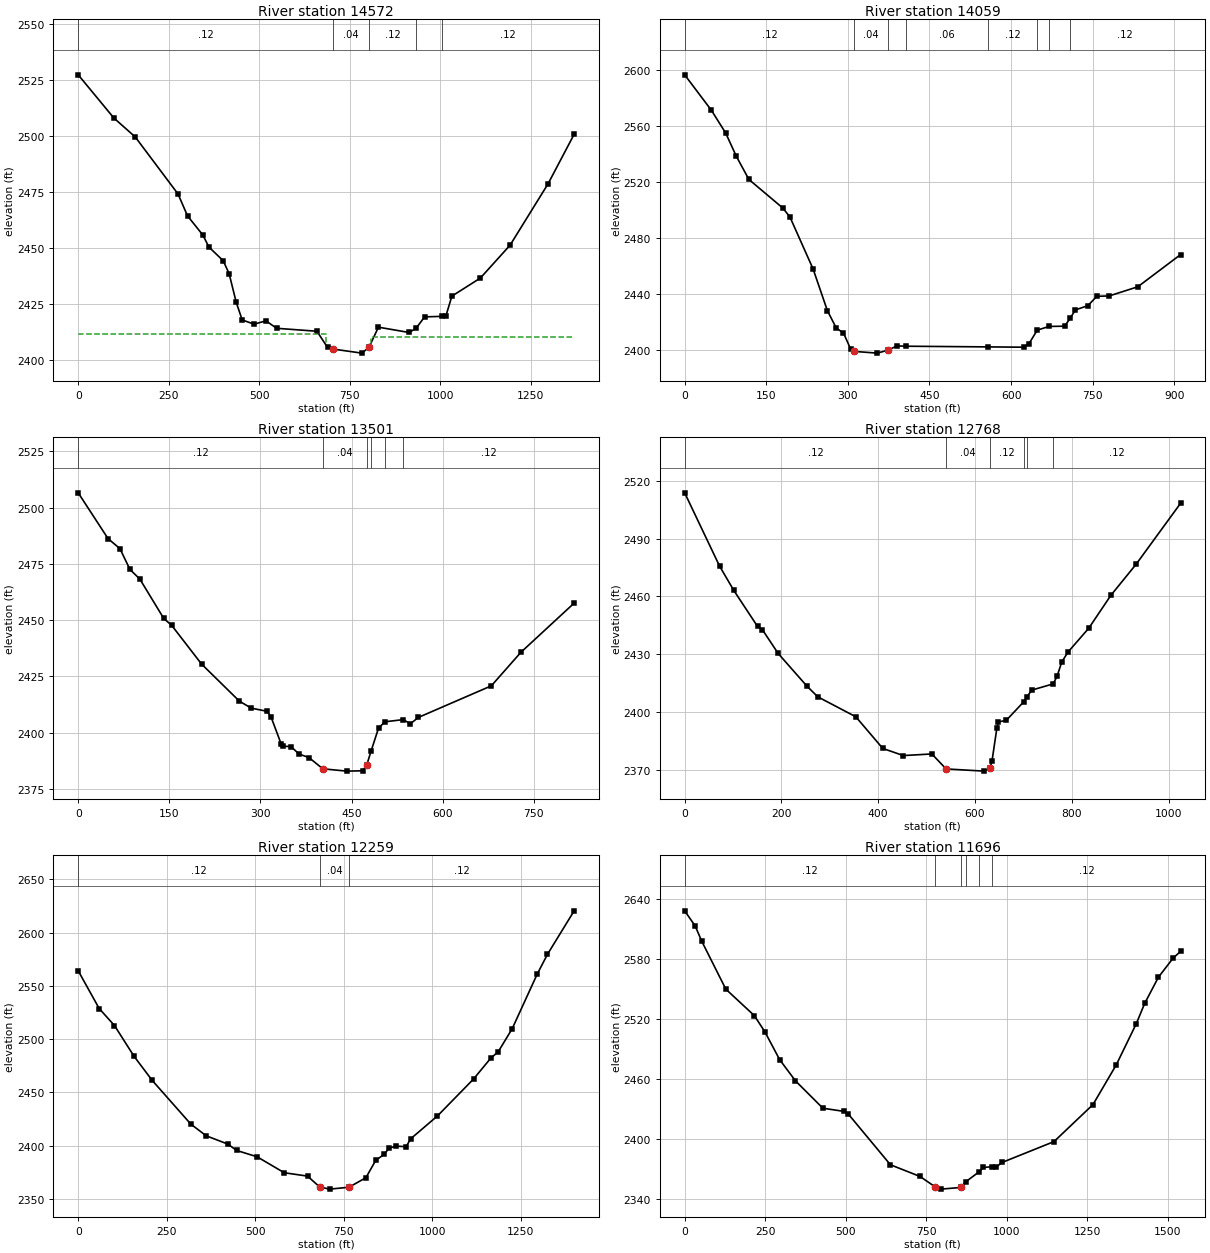
Type RM Length L Ch R = 1 ,14572   ,566.3,512.4,455.1
XS GIS Cut Line= 4
     2109266.211      456810.821     2108725.651       457093.82
     2108426.754      457176.494     2108305.923      457608.941
#Sta/Elev= 30
       0 2527.38    98.4 2508.08   157.5  2499.6   275.6 2474.11   301.8 2464.34
   344.4 2455.71   360.8 2450.41   400.2 2444.31   416.6 2438.55   436.3 2425.68
   452.7 2417.84   485.5 2415.93   518.3 2417.43   547.8 2414.09   659.1 2412.77
   688.5 2405.51   704.8 2404.78   783.2 2402.99   802.8 2405.58   828.9 2414.59
   913.8 2412.21  933.25 2414.15   956.3 2419.19 1005.33 2419.43  1015.3 2419.67
  1031.7 2428.46  1110.4 2436.55  1192.3 2451.22  1297.2 2478.65  1369.3 2500.82
#Mann= 5 ,-1 , 0
       0     .12       0   704.8     .04       0   802.8     .12       0
  933.25    .016       0 1005.33     .12       0
#XS Ineff= 2 , 0
           683.1 2411.41  807.02         2410.42
Permanent Ineff=
       F       F
Bank Sta=704.8,802.8
XS Rating Curve= 0 ,0
Exp/Cntr=0.5,0.3

Type RM Length L Ch R = 1 ,14059   ,556.5,558.3,569.1
XS GIS Cut Line= 2
      2108083.34      456623.215     2108264.586      457516.728
#Sta/Elev= 30
       0 2596.45    49.2  2571.1    75.4 2554.87    95.1 2538.18   118.1 2521.74
   180.4 2501.37   193.5 2494.96   236.1 2457.82   262.4 2428.03   278.8 2415.61
   291.9 2412.17     305 2400.77   311.6 2399.01   354.2 2397.78   373.9 2399.94
   390.3 2402.93  407.03 2402.71  557.72 2402.23   623.1 2402.01     633 2404.55
  648.13  2414.2  669.86 2416.84   698.5 2417.01  708.41 2422.51   718.2 2428.63
   741.2 2431.66   757.6 2438.31   780.5 2438.63     833 2445.14   911.7 2468.15
#Mann= 8 ,-1 , 0
       0     .12       0   311.6     .04       0   373.9     .12       0
  407.03     .06       0  557.72     .12       0  648.13     .08       0
  669.86    .016       0  708.41     .12       0
Bank Sta=311.6,373.9
XS Rating Curve= 0 ,0
Exp/Cntr=0.3,0.1

Type RM Length L Ch R = 1 ,13501   ,695.9,733.3,755.4
XS GIS Cut Line= 3
      2107673.15      456877.596     2107759.004      457434.054
      2107809.88      457682.076
#Sta/Elev= 30
       0 2506.58    49.1 2486.24    68.7 2481.78    85.1 2472.56   101.5 2468.25
   140.8 2450.78   153.8 2447.72     203 2430.53   265.2 2414.06   284.8 2410.94
     311 2409.54   317.5 2406.92   333.9  2395.1   337.2 2394.05   350.3 2393.86
   363.4 2390.56   379.7    2389   402.6    2384   441.9 2382.97   468.1 2383.12
   474.7 2385.58   482.3 2392.13   494.3 2402.12  504.87 2404.89  534.76 2405.84
   546.7 2404.01   559.8 2406.82   679.9 2420.86   728.6 2435.76   816.2  2457.6
#Mann= 6 ,-1 , 0
       0     .12       0   402.6     .04       0   474.7     .04       0
   482.3     .08       0  504.87    .016       0  534.76     .12       0
Bank Sta=402.6,474.7
XS Rating Curve= 0 ,0
Exp/Cntr=0.3,0.1

Type RM Length L Ch R = 1 ,12768   ,497.2,508.1,514.2
XS GIS Cut Line= 2
     2107355.174       456696.35     2106805.075      457561.245
#Sta/Elev= 30
       0  2513.8      72  2475.8   101.5 2463.12   150.6 2444.42   160.5 2442.77
   193.2 2430.38   252.2 2413.54   275.1 2407.86   353.7  2397.5   409.4 2381.06
   451.9 2377.35   510.9 2378.19   540.3 2370.41   618.9 2369.27  631.13 2370.95
   635.3 2374.72   645.1 2391.41   648.4  2394.8   664.8 2395.68  701.14 2405.38
  706.57 2407.54   717.2 2411.33  761.61 2414.58   769.6 2418.51   779.4 2425.97
   792.5 2431.19   835.1 2443.47   880.9 2460.58   933.3  2476.8    1025  2508.4
#Mann= 6 ,-1 , 0
       0     .12       0   540.3     .04       0  631.13     .12       0
  701.14     .08       0  706.57    .016       0  761.61     .12       0
Bank Sta=540.3,631.13
XS Rating Curve= 0 ,0
Exp/Cntr=0.3,0.1

Type RM Length L Ch R = 1 ,12259   ,560,563,562.3
XS GIS Cut Line= 2
2107155.31103484456332.1597345722106197.06040387457353.730891819
#Sta/Elev= 30
       0 2564.11    59.2  2528.7   102.4 2512.71   157.9 2483.73     209 2461.17
     318 2420.14   361.3 2409.18   422.5 2401.36   447.6 2395.37   505.2 2389.44
   581.9 2374.46   647.7 2371.28   682.4 2360.98   710.3 2359.06   764.6 2360.83
   812.5 2369.77   840.3 2386.08   864.9 2391.91   877.5 2397.53   898.3 2399.47
   926.2 2398.88   938.8 2406.29  1014.4 2427.72  1116.5 2462.46  1165.3 2482.09
  1186.2 2488.06  1225.6 2509.66  1296.5 2561.13  1325.4 2579.63  1400.7 2620.45
#Mann= 3 , 0 , 0
       0     .12       0   682.4     .04       0   764.6     .12       0
Bank Sta=682.4,764.6
XS Rating Curve= 0 ,0
Exp/Cntr(USF)=0,0
Exp/Cntr=0.3,0.1

Type RM Length L Ch R = 1 ,11696   ,881.3,882.6,883.1
XS GIS Cut Line= 2
     2106817.794      455901.409     2105739.855      457001.607
#Sta/Elev= 30
       0  2627.8    32.8 2612.61    52.4 2597.88   127.8 2549.69   216.3 2523.31
   249.1 2507.17   294.9 2479.44   344.1 2458.24   429.3 2430.95   494.8  2427.8
     508 2425.21     639 2374.56   730.8 2362.92   776.7 2352.81   796.3 2350.27
   858.6 2351.97   872.9 2357.56   913.5 2367.34   927.4 2371.84  955.71  2372.7
   966.8  2372.3   986.4 2376.95    1147 2397.66  1268.2 2434.62  1340.4 2474.19
  1402.6 2515.25  1428.8 2535.55  1471.4 2561.61  1517.3 2580.77  1540.3 2587.36
#Mann= 6 ,-1 , 0
       0     .12       0   776.7     .04       0   858.6     .04       0
   872.9     .12       0   913.5    .016       0  955.71     .12       0
Bank Sta=776.7,858.6
XS Rating Curve= 0 ,0
Exp/Cntr=0.3,0.1

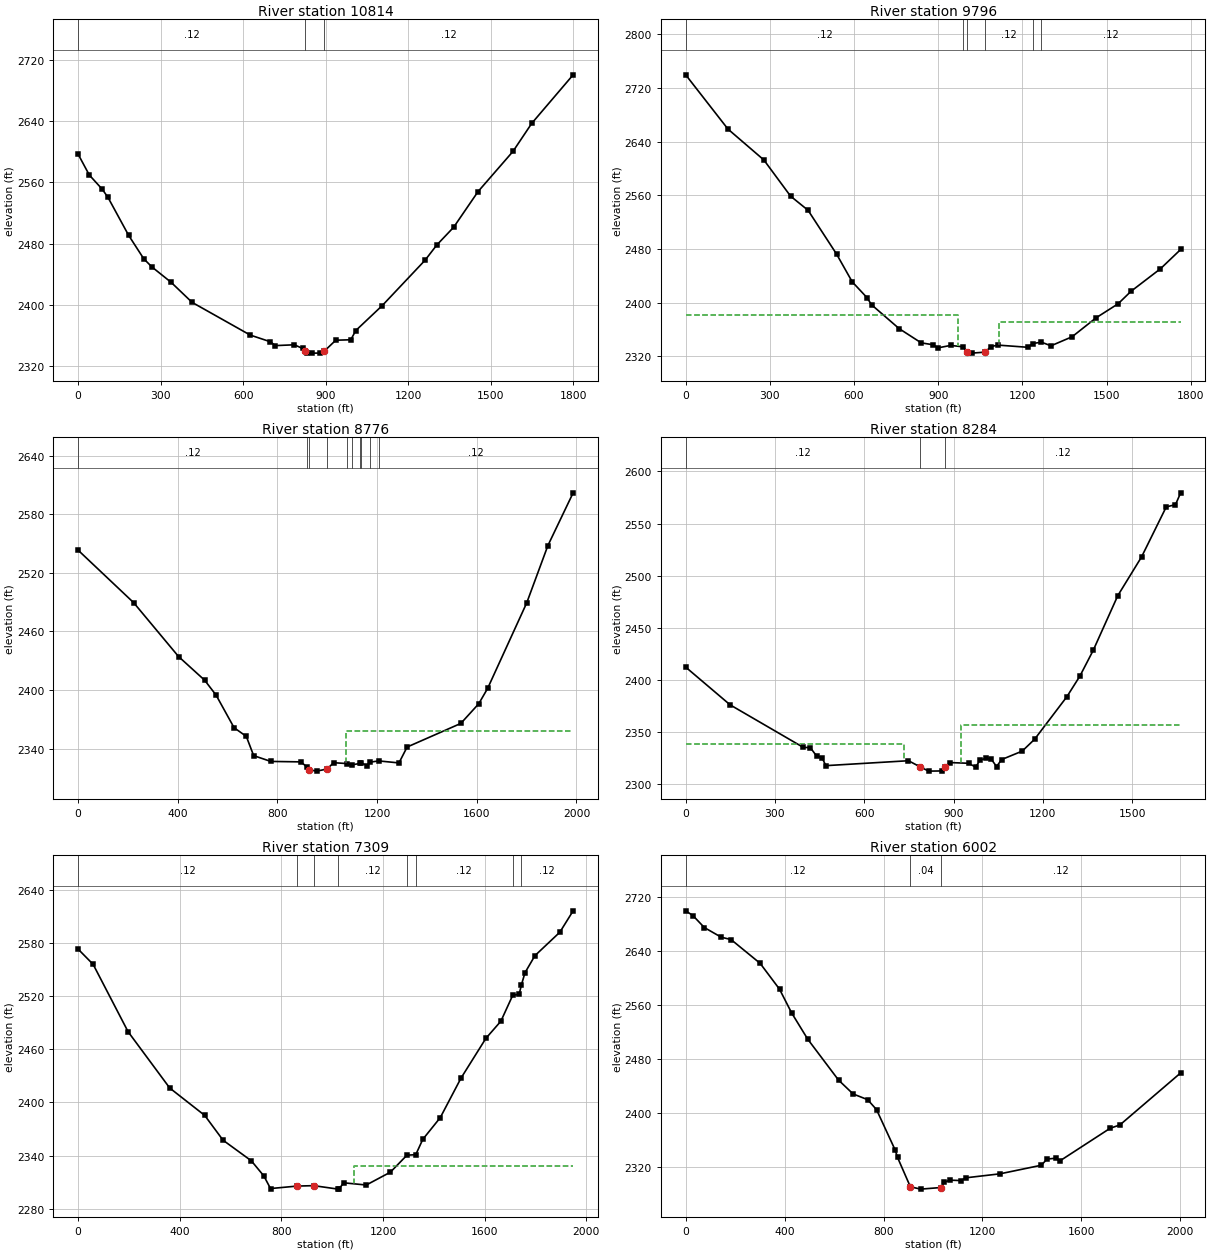
Type RM Length L Ch R = 1 ,10814   ,987.1,1018,1020.5
XS GIS Cut Line= 2
2106235.05271964455268.3748931412104943.31398361456522.121313399
#Sta/Elev= 30
       0 2596.59    40.5 2569.54    87.7 2550.96   108.6 2540.23   183.4 2490.98
   238.5 2460.34   268.2 2449.67   337.7 2429.74   414.2 2403.52   625.7 2360.85
   698.8 2352.15   717.1 2347.11   786.4 2348.17   816.2 2343.39   824.1 2340.09
   831.4 2337.69   848.7  2337.3   881.2 2337.35   895.1 2339.89   936.8 2354.12
   991.5 2354.74  1009.7 2366.76  1105.8 2399.28  1261.2 2458.29  1304.5  2478.4
  1365.8 2501.53  1454.2 2547.91  1581.3 2600.33  1649.8 2637.02  1800.1 2700.18
#Mann= 3 , 0 , 0
       0     .12       0   824.1     .04       0   895.1     .12       0
Bank Sta=824.1,895.1
XS Rating Curve= 0 ,0
Exp/Cntr(USF)=0,0
Exp/Cntr=0.3,0.1

Type RM Length L Ch R = 1 ,9796    ,1034,1020.2,1014.7
XS GIS Cut Line= 2
     2106144.889      454680.241     2104465.591      455221.106
#Sta/Elev= 30
       0 2739.49   150.8 2658.59   278.7 2612.61   373.8 2558.74   436.1 2537.68
   537.8 2472.38   593.6 2431.02     646 2407.61   662.4  2396.9   760.8 2361.35
   839.5 2340.13   882.1 2337.28   898.5 2332.63   944.4 2336.33  988.73 2334.23
  1003.5 2326.24  1019.8 2324.84  1065.8 2326.28  1088.7 2334.55  1111.7 2336.83
  1219.9 2333.52 1236.98 2339.17 1268.01 2341.14  1301.9 2335.75  1377.3 2349.22
  1462.6  2377.4  1541.3 2398.39  1587.2 2416.96  1692.1 2450.52  1764.2 2479.26
#Mann= 6 ,-1 , 0
       0     .12       0  988.73     .04       0  1003.5     .04       0
  1065.8     .12       0 1236.98    .016       0 1268.01     .12       0
#XS Ineff= 2 , 0
           969.7 2381.63 1116.07         2370.83
Permanent Ineff=
       F       F
Bank Sta=1003.5,1065.8
XS Rating Curve= 0 ,0
Exp/Cntr=0.3,0.1

Type RM Length L Ch R = 1 ,8776    ,481.2,492.1,505
XS GIS Cut Line= 3
     2105486.255      453541.808     2104417.611      454283.316
     2103990.153      454819.819
#Sta/Elev= 30
       0 2543.24   222.8  2489.5     403 2434.31   507.8 2410.04   553.7 2394.76
   625.8 2361.44   674.9 2352.52   704.4 2332.82   773.2 2326.89   894.4 2326.42
  919.05 2320.91   927.2 2318.31   956.7 2316.95   998.5 2319.05  1025.5 2325.57
 1079.32  2324.7  1098.8  2323.4 1131.13 2324.82 1134.75 2325.59  1159.8 2322.58
  1170.7 2326.13 1206.65  2327.4  1287.6 2325.36  1320.3 2341.63  1535.9 2365.82
  1607.8 2385.96  1643.7 2401.81  1800.5 2489.38  1885.4 2548.04  1986.7 2602.04
#Mann= 10 ,-1 , 0
       0     .12       0  919.05     .04       0   927.2     .04       0
   998.5     .12       0 1079.32     .08       0  1098.8     .12       0
 1131.13     .06       0 1134.75     .12       0  1170.7    .016       0
 1206.65     .12       0
#XS Ineff= 2 , 0
                         1075.18         2357.56
Permanent Ineff=
       F       F
Bank Sta=927.2,998.5
XS Rating Curve= 0 ,0
Exp/Cntr=0.3,0.1

Type RM Length L Ch R = 1 ,8284    ,985.4,974.6,976
XS GIS Cut Line= 2
2105209.26019397 453423.63689431 2103630.4684055453947.086578188
#Sta/Elev= 30
       0 2412.09   149.3 2375.87   394.7  2335.1     419 2334.73   439.6 2326.79
   457.9 2325.28   470.9 2317.48   748.6 2322.21   787.6 2316.34   816.4 2312.22
   861.3 2312.41   870.6 2315.84     889 2320.44   951.2 2319.75   974.5    2316
   989.2 2322.93  1009.9  2324.5  1027.2 2323.56  1044.6 2316.63  1061.8 2323.35
  1130.9 2331.45  1172.4 2342.81  1280.8 2383.63  1324.5  2403.4  1369.4 2428.21
  1452.1 2480.79  1531.9 2517.94  1614.8 2565.94  1645.9 2568.15  1663.3 2579.48
#Mann= 3 , 0 , 0
       0     .12       0   787.6     .04       0   870.6     .12       0
#XS Ineff= 2 , 0
          734.82 2337.82  926.24          2356.9
Permanent Ineff=
       F       F
Bank Sta=787.6,870.6
XS Rating Curve= 0 ,0
Exp/Cntr(USF)=0,0
Exp/Cntr=0.3,0.1

Type RM Length L Ch R = 1 ,7309    ,1273.7,1306.4,1307.2
XS GIS Cut Line= 3
     2104980.285      452307.415     2103911.641      452887.536
     2103287.901      453271.376
#Sta/Elev= 30
       0 2573.08      59 2555.89   196.6 2479.84   360.5  2416.3   498.2 2385.37
   570.3  2357.4   681.7 2334.12   730.9 2317.05   757.1 2302.82     862 2305.62
   927.5 2306.09 1022.84 2302.19  1025.9 2302.17  1045.5 2309.31    1134  2306.8
    1229 2321.32 1294.12 2340.49  1328.8 2341.05  1356.5 2358.38  1425.2 2382.86
  1506.9  2427.5    1605 2472.44  1663.9 2491.78  1710.3  2520.9  1735.8 2522.24
 1744.98 2532.98  1758.7 2546.47  1797.9 2565.75    1896 2592.25  1948.3 2616.37
#Mann= 8 ,-1 , 0
       0     .12       0     862     .04       0   927.5     .06       0
 1022.84     .12       0 1294.12    .016       0  1328.8     .12       0
  1710.3    .016       0 1744.98     .12       0
#XS Ineff= 2 , 0
                         1084.05         2328.57
Permanent Ineff=
       F       F
Bank Sta=862,927.5
XS Rating Curve= 0 ,0
Exp/Cntr=0.3,0.1

Type RM Length L Ch R = 1 ,6002    ,428.7,400.4,397.5
XS GIS Cut Line= 4
     2104848.271      451691.552     2104040.896      451664.431
     2103775.943       451731.19     2103009.443      452241.289
#Sta/Elev= 30
       0 2699.49    29.4 2692.42    75.2 2674.74   143.9  2660.3   183.2 2656.93
   300.9 2621.64   379.4 2583.29   428.4 2548.05   493.9 2508.87   618.1 2448.39
     677  2427.8   735.9 2419.32   771.8 2404.54   846.9 2344.81   856.6 2333.72
   908.7 2289.97     951 2286.59  1032.3 2288.98  1045.3 2296.68    1068 2299.92
  1113.8 2299.27  1133.5 2303.41  1271.1 2309.29  1438.2 2322.03  1461.2 2331.15
  1497.2 2332.48  1513.6 2328.53  1716.7  2376.9    1756 2381.81  2001.8 2459.02
#Mann= 3 ,-1 , 0
       0     .12       0   908.7     .04       0  1032.3     .12       0
Bank Sta=908.7,1032.3
XS Rating Curve= 0 ,0
Exp/Cntr=0.3,0.1

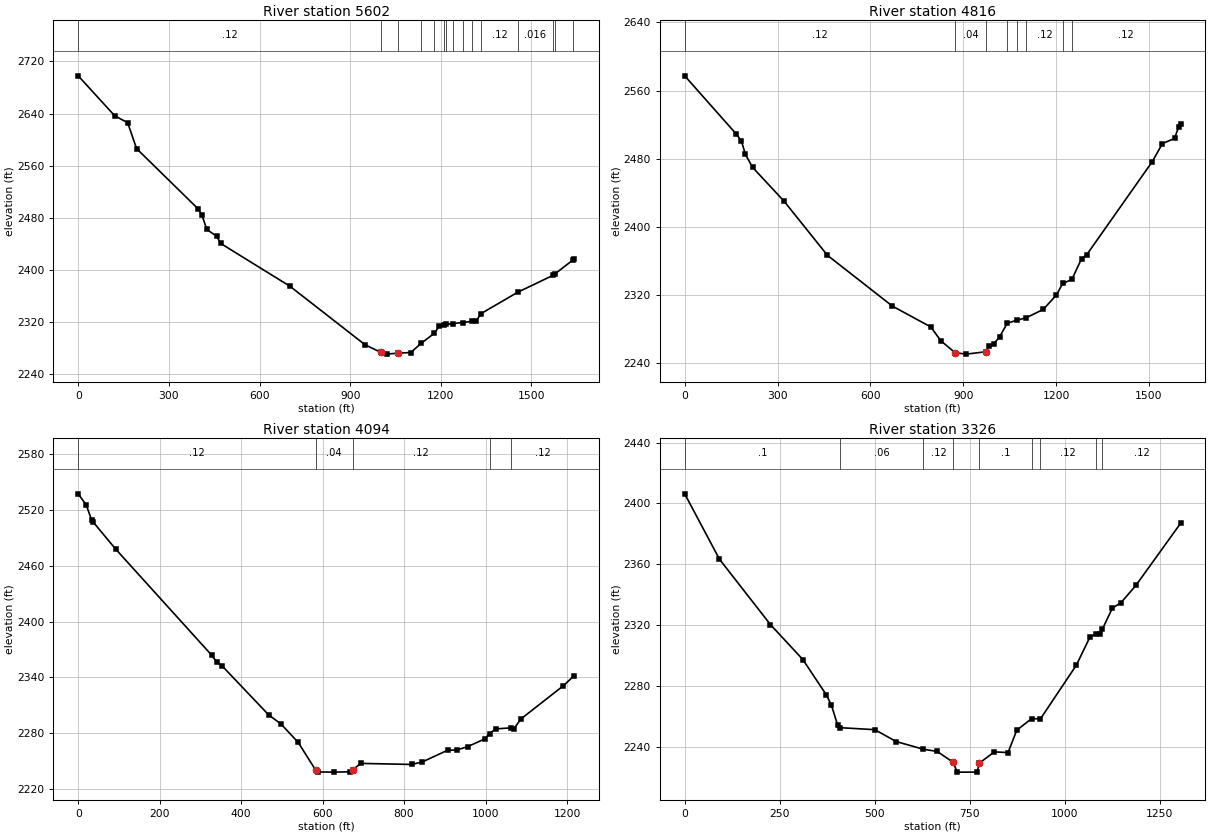
Type RM Length L Ch R = 1 ,5602    ,731.7,785.9,788.5
XS GIS Cut Line= 4
      2104675.86        451226.5     2103758.944      451334.676
     2103467.901      451445.427     2103073.833      451545.875
#Sta/Elev= 30
       0 2697.81   121.1  2636.4   163.7 2625.98   193.2 2586.19   396.2 2494.11
   409.2 2484.66   425.6 2462.23   458.4 2451.74   471.5 2440.81   700.6 2375.23
   949.5 2285.38    1002 2273.73  1021.6 2271.08  1057.7 2272.63  1100.3 2273.46
 1135.69 2287.79 1178.76 2303.09  1195.3 2314.35 1210.37 2316.21 1218.74 2316.64
 1241.71    2318 1272.19 2319.55 1302.67 2321.36  1316.7 2321.96 1333.15 2333.19
 1455.08 2366.09 1570.47 2391.67    1577 2393.75 1637.96 2415.67  1641.4 2416.88
#Mann= 15 ,-1 , 0
       0     .12       0    1002     .04       0  1057.7     .12       0
 1135.69    .016       0 1178.76     .12       0 1210.37     .06       0
 1218.74     .12       0 1241.71     .08       0 1272.19    .016       0
 1302.67     .06       0 1333.15     .12       0 1455.08    .016       0
 1570.47     .06       0    1577    .016       0 1637.96     .12       0
Bank Sta=1002,1057.7
XS Rating Curve= 0 ,0
Exp/Cntr=0.3,0.1

Type RM Length L Ch R = 1 ,4816    ,697.2,722.2,729.2
XS GIS Cut Line= 3
      2104611.47       450927.73     2103563.198      450628.959
     2103050.652      450618.657
#Sta/Elev= 30
       0 2577.23   166.9 2508.89   183.3 2500.74   196.4 2485.07   219.3 2469.95
   320.8 2430.39   461.5  2366.7     671 2307.28   795.4 2282.75   828.2 2266.41
     874 2252.57     910 2250.91   972.2 2253.65     982 2260.07   998.4 2262.69
    1018 2271.36 1042.64 2287.27 1073.35 2290.63 1103.53 2293.55  1158.6 2303.29
    1201 2320.07  1221.7 2333.78 1251.24 2338.43  1282.7 2362.91    1299 2367.32
  1511.2 2476.66  1543.9 2497.78  1583.1 2503.86  1596.1 2517.24  1602.7 2520.25
#Mann= 8 ,-1 , 0
       0     .12       0     874     .04       0   972.2     .12       0
 1042.64    .016       0 1073.35     .08       0 1103.53     .12       0
  1221.7    .016       0 1251.24     .12       0
Bank Sta=874,972.2
XS Rating Curve= 0 ,0
Exp/Cntr=0.3,0.1

Type RM Length L Ch R = 1 ,4094    ,771,767.8,757.9
XS GIS Cut Line= 2
     2104743.685      450515.919     2103724.889      449849.123
#Sta/Elev= 30
       0 2537.46    19.6 2525.51    32.7 2509.66      36 2507.49    91.6 2478.17
   327.3 2364.06   340.4 2356.28   353.5 2352.25   468.1 2299.41   497.5 2290.03
   540.1 2270.03   582.6 2240.48   589.2 2238.26   628.4 2238.08   667.7 2238.46
   674.3 2240.73   693.9 2247.47   818.3 2246.34   844.5 2248.98   906.7 2261.57
   929.6 2261.95   955.8 2265.42   998.3 2273.85 1009.79 2279.44  1024.5 2284.52
 1063.73 2285.78  1070.3 2284.98  1086.7 2295.19  1191.4 2331.11  1217.6 2341.91
#Mann= 5 ,-1 , 0
       0     .12       0   582.6     .04       0   674.3     .12       0
 1009.79    .016       0 1063.73     .12       0
Bank Sta=582.6,674.3
XS Rating Curve= 0 ,0
Exp/Cntr=0.3,0.1

Type RM Length L Ch R = 1 ,3326    ,3341.8,3326.3,3311.2
XS GIS Cut Line= 3
     2104889.889      449828.194      2104117.85      449334.503
     2103810.642      449096.504
#Sta/Elev= 30
       0 2406.28    91.6 2363.26   225.8 2320.27   310.9 2297.33   373.1 2273.96
   386.2 2267.27   402.6 2254.13   409.1 2252.53   500.7  2251.2   556.4 2243.42
   628.4 2238.33   664.4 2236.91   706.9  2229.7   716.8  2223.3   769.1  2223.3
   775.7 2229.28   814.9 2236.61   850.9 2236.16   873.8 2250.84   913.1 2258.52
     936 2258.27  1030.7 2293.65  1066.6  2312.2  1082.9 2314.14  1092.7 2314.12
  1099.3 2317.35  1125.4 2331.13  1148.2 2334.74  1187.4 2346.09    1305 2386.93
#Mann= 9 ,-1 , 0
       0      .1       0   409.1     .06       0   628.4     .12       0
   706.9     .04       0   775.7      .1       0   913.1    .016       0
     936     .12       0  1082.9    .016       0  1099.3     .12       0
Bank Sta=706.9,775.7
XS Rating Curve= 0 ,0
Exp/Cntr=0.3,0.1
LCMann Table=0

Chan Stop Cuts=-1
Use User Specified Reach Order=0
Composite Channel Slope=5